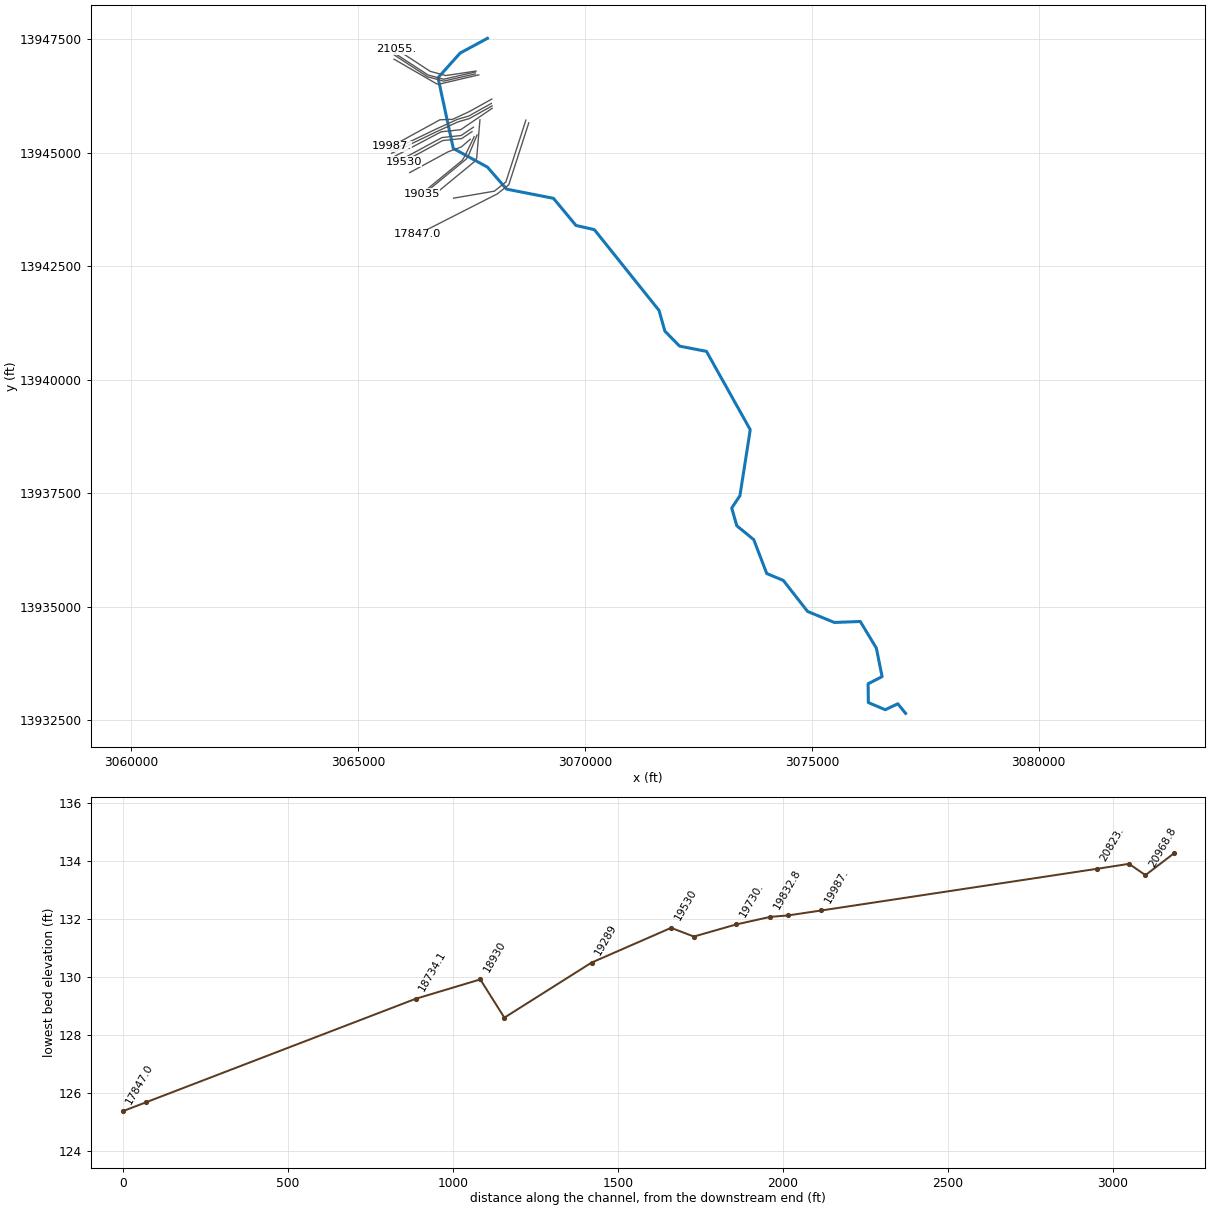
--- K131-00-00.prj (project) ---

Proj Title=K131-00-00
Current Plan=p11
Default Exp/Contr=0.3,0.1
English Units
Geom File=g04
Flow File=f10
Flow File=f11
Plan File=p10
Plan File=p11
Y Axis Title=Elevation
X Axis Title(PF)=Main Channel Distance
X Axis Title(XS)=Station
BEGIN DESCRIPTION:
Cypress Creek Watershed
Spring Gully
HCFCD Unit K131-00-00
Flood Hazard Model
10, 2, 1, 0.2%
Filename K131-00-00
Prepared by:  Halff Associates  DATE:  03/26/04
Reviewed by:  _____________________  DATE:  __________________
STATUS (Final)
TROPICAL STORM ALLISON RECOVERY PROJECT
END DESCRIPTION:
DSS File=dss
DSS Export Rating Curves= 0
DSS Export Rating Curve Sorted= 0
DSS Export Volume Flow Curves= 0
DXF OffsetX= 0
DXF OffsetY= 0
DXF ScaleX= 1
DXF ScaleY= 10

--- K131-00-00.p11 (plan) ---

Plan Title=Effective MP 2013
Program Version=3.13
Short Identifier=Eff MP 2013
Geom File=g04
Flow File=f11
Subcritical Flow
K Sum by GR= 0
Std Step Tol= 0.01
Critical Tol= 0.01
Num of Std Step Trials= 40
Max Error Tol= 0.3
Flow Tol Ratio= 0.001
Split Flow NTrial= 30
Split Flow Tol= 0.02
Split Flow Ratio= 0.02
Log Output Level= 0
Friction Slope Method= 1
Unsteady Friction Slope Method= 2
Unsteady Bridges Friction Slope Method= 1
Calc Critical at every XS
Secant Critical Depth
Global Vel Dist= 0 , 0 , 0
Global Log Level= 0
CheckData=True
Encroach Param=-1 ,0,0, 2
BEGIN DESCRIPTION:
FEMA Effective MP October 2013
END DESCRIPTION:
Computation Interval=1HOUR
Output Interval=1HOUR
Run HTab= 0
Run UNet= 0
Run PostProcess= 0
UNET Theta= 1
UNET Theta Warmup= 1
UNET ZTol= 0.02
UNET ZSATol= 0.1
UNET MxIter= 20
UNET MaxInSteps= 20
UNET DtIC= 0
UNET DtMin= 0
UNET MaxCRTS= 20
UNET WFStab= 2
UNET SFStab= 1
UNET WFX= 1
UNET SFX= 1
UNET DSS MLevel= 4
UNET DZMax Abort= 100
UNET Convert EG Bridges=-1
UNET Use Existing IB Tables=-1
UNET Froude Reduction=False
UNET Froude Limit= 1
UNET Froude Power= 10
Instantaneous Interval=1HOUR
DSS File=dss
Write IC File= 0
IC Time=0,,
Echo Input=False
Echo Output=False
Write Detailed= 0
Detailed Automatic Start=False, 10

--- K131-00-00.p10 (plan) ---

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Plan Title=Effective FW 2013
Short Identifier=Eff FW 2013
Geom File=g04
Flow File=f10
Encroach River=K131-00-00
Encroach Reach=K131-00-00_0022
Encroach Node=21055.
       1 4900.45 5100.45
Encroach Node=20968.8
       1 4900.45 5100.45
Encroach Node=20919.2
       1 4900.45 5100.45
Encroach Node=20823.
       1 4900.45 5100.45
Encroach Node=19987.
       1 4848.45 5148.45
Encroach Node=19887.1
       1 4798.45 5198.45
Encroach Node=19832.8
       1 4798.45 5198.45
Encroach Node=19730.
       1 4798.45 5198.45
Encroach Node=19599
       1 5079.75 5192.87
Encroach Node=19530
       1 5073.93 5161.81
Encroach Node=19289
       1 5017.37 5133.02
Encroach Node=19035
       1 4803.55 4959.97
Encroach Node=18930
       1  4917.2 5056.86
Encroach Node=18734.1
       1 4963.26 5053.16
Encroach Node=17918.
       1    4891    5019
Encroach Node=17847.0
       1    4891    5019
Encroach Node=17787.5
       1    4891    5019
Encroach Node=17656.3
       1 4891.24  5029.3
Encroach Node=17612.3
       1 4891.24  5024.3
Encroach Node=17487.
       1 4891.24  5036.9
Encroach Node=17252
       1 4893.54 5136.28
Encroach Node=17137.6
       1 4893.54 5136.28
Encroach Node=17100.9
       1 4927.53 5090.37
Encroach Node=16991.
       1 4713.51 5022.26
Encroach Node=15980.8
       1  4977.5  5014.2
Encroach Node=14914.9
       1    4959  5042.9
Encroach Node=13844.3
       1  4956.2  5045.6
Encroach Node=12515.1
       1    4960  5036.7
Encroach Node=11192.9
       1  4956.5  5041.7
Encroach Node=10383
       1  4944.2  5044.2
Encroach Node=10302.7
       1  4953.1  5046.3
Encroach Node=10232.4
       1  4953.1  5046.3
Encroach Node=10118.
       1  4944.6  5066.8
Encroach Node=9351.
       1  4949.1  5049.1
Encroach Node=9273.7
       1  4941.1  5109.1
Encroach Node=9136.0
       1  4941.1  5109.1
Encroach Node=9034.
       1  4964.4  5084.4
Encroach Node=8400
       1 4945.57 5051.01
Encroach Node=7394.8
       1  4957.1  5042.3
Encroach Node=6262.
       1  4946.4  5056.4
Encroach Node=6187.7
       1  4926.8  5059.9
Encroach Node=6165.5
       1 4900.49    5100
Encroach Node=6070.
       1 4900.49    5100
Encroach Node=5838.4
       1    4830    5100
Encroach Node=3950.0
       1 4849.43    5100
Encroach Node=3369
       1 4614.55  5105.1
Encroach Node=3264.7
       1    4580  5105.1
Encroach Node=3144.4
       1    4600  5105.1
Encroach Node=3044.
       1 4614.55  5105.1
Encroach Node=2169.2
       1    3867    5162
FEMA Effective Floodway October 2013

--- K131-00-00.f11 (steady flow) ---

Flow Title=Effective MP 2013
Program Version=3.13
Number of Profiles= 4
Profile Names=10PCT_10yr,2PCT_50yr,1PCT_100yr,0.2PCT_500yr
River Rch & RM=K131-00-00,K131-00-00_0022       ,21055.
     353     541     665     937
River Rch & RM=K131-00-00,K131-00-00_0022       ,19987.
     424     658     797    1130
River Rch & RM=K131-00-00,K131-00-00_0022       ,18734.1
     500     773     940    1341
River Rch & RM=K131-00-00,K131-00-00_0022       ,17918.
     614     956    1156    1662
River Rch & RM=K131-00-00,K131-00-00_0022       ,17252
     667    1041    1255    1810
River Rch & RM=K131-00-00,K131-00-00_0022       ,15980.8
     789    1236    1484    2154
River Rch & RM=K131-00-00,K131-00-00_0022       ,14914.9
     941    1483    1770    2587
River Rch & RM=K131-00-00,K131-00-00_0022       ,13844.3
    1124    1780    2114    3110
River Rch & RM=K131-00-00,K131-00-00_0022       ,12515.1
    1238    1955    2314    3401
River Rch & RM=K131-00-00,K131-00-00_0022       ,11192.9
    1363    2145    2532    3718
River Rch & RM=K131-00-00,K131-00-00_0022       ,10383
    1474    2314    2724    3997
River Rch & RM=K131-00-00,K131-00-00_0022       ,9351.
    1595    2497    2933    4300
River Rch & RM=K131-00-00,K131-00-00_0022       ,7394.8
    1797    2802    3279    4802
River Rch & RM=K131-00-00,K131-00-00_0022       ,6262.
    1979    3076    3588    5250
River Rch & RM=K131-00-00,K131-00-00_0022       ,5838.4
    4482    6944    8222   11934
Boundary for River Rch & Prof#=K131-00-00,K131-00-00_0022       , 1
Up Type= 0
Dn Type= 3
Dn Slope=0.0011
Boundary for River Rch & Prof#=K131-00-00,K131-00-00_0022       , 2
Up Type= 0
Dn Type= 3
Dn Slope=0.0011
Boundary for River Rch & Prof#=K131-00-00,K131-00-00_0022       , 3
Up Type= 0
Dn Type= 3
Dn Slope=0.0011
Boundary for River Rch & Prof#=K131-00-00,K131-00-00_0022       , 4
Up Type= 0
Dn Type= 3
Dn Slope=0.0011
DSS Import GetInterval= 0
DSS Import GetPeak= 0
DSS Import FillOption= 0

--- K131-00-00.f10 (steady flow) ---

Flow Title=Effective FW 2013
Program Version=3.13
Number of Profiles= 2
Profile Names=1PCT_100yr,1PCTFloodway_10
River Rch & RM=K131-00-00,K131-00-00_0022       ,21055.
     665     665
River Rch & RM=K131-00-00,K131-00-00_0022       ,19987.
     797     797
River Rch & RM=K131-00-00,K131-00-00_0022       ,18734.1
     940     940
River Rch & RM=K131-00-00,K131-00-00_0022       ,17918.
    1156    1156
River Rch & RM=K131-00-00,K131-00-00_0022       ,17252
    1255    1255
River Rch & RM=K131-00-00,K131-00-00_0022       ,15980.8
    1484    1484
River Rch & RM=K131-00-00,K131-00-00_0022       ,14914.9
    1770    1770
River Rch & RM=K131-00-00,K131-00-00_0022       ,13844.3
    2114    2114
River Rch & RM=K131-00-00,K131-00-00_0022       ,12515.1
    2314    2314
River Rch & RM=K131-00-00,K131-00-00_0022       ,11192.9
    2532    2532
River Rch & RM=K131-00-00,K131-00-00_0022       ,10383
    2724    2724
River Rch & RM=K131-00-00,K131-00-00_0022       ,9351.
    2933    2933
River Rch & RM=K131-00-00,K131-00-00_0022       ,7394.8
    3279    3279
River Rch & RM=K131-00-00,K131-00-00_0022       ,6262.
    3588    3588
River Rch & RM=K131-00-00,K131-00-00_0022       ,5838.4
    8222    8222
Boundary for River Rch & Prof#=K131-00-00,K131-00-00_0022       , 1
Up Type= 0
Dn Type= 1
Dn Known WS=103.59
Boundary for River Rch & Prof#=K131-00-00,K131-00-00_0022       , 2
Up Type= 0
Dn Type= 1
Dn Known WS=104.59
DSS Import GetInterval= 0
DSS Import GetPeak= 0
DSS Import FillOption= 0

--- K131-00-00.g04 (geometry) ---

Geom Title=K131-00-00 2013
Program Version=3.13

River Reach=K131-00-00      ,K131-00-00_0022
Reach XY= 30
      3067849.75       13947523.        3067248.       13947198.
      3066761.26     13946654.89      3067097.75       13945096.
      3067849.75       13944685.      3068271.55     13944199.76
      3069305.19     13943997.15      3069801.58      13943399.1
       3070206.5     13943306.09      3071632.42     13941525.47
      3071760.01     13941071.19      3072083.81     13940739.88
      3072676.76     13940624.09      3073642.25       13938897.
      3073414.31     13937443.05      3073233.75     13937171.35
      3073345.73     13936780.72      3073718.99     13936475.17
      3074005.28     13935728.34      3074371.92     13935575.37
      3074904.63      13934893.2      3075493.17     13934650.14
        3076067.       13934671.      3076420.96     13934084.72
      3076547.86      13933455.7       3076239.7     13933298.58
      3076244.91     13932884.52      3076617.31     13932726.53
      3076894.22     13932857.61      3077065.75       13932646.

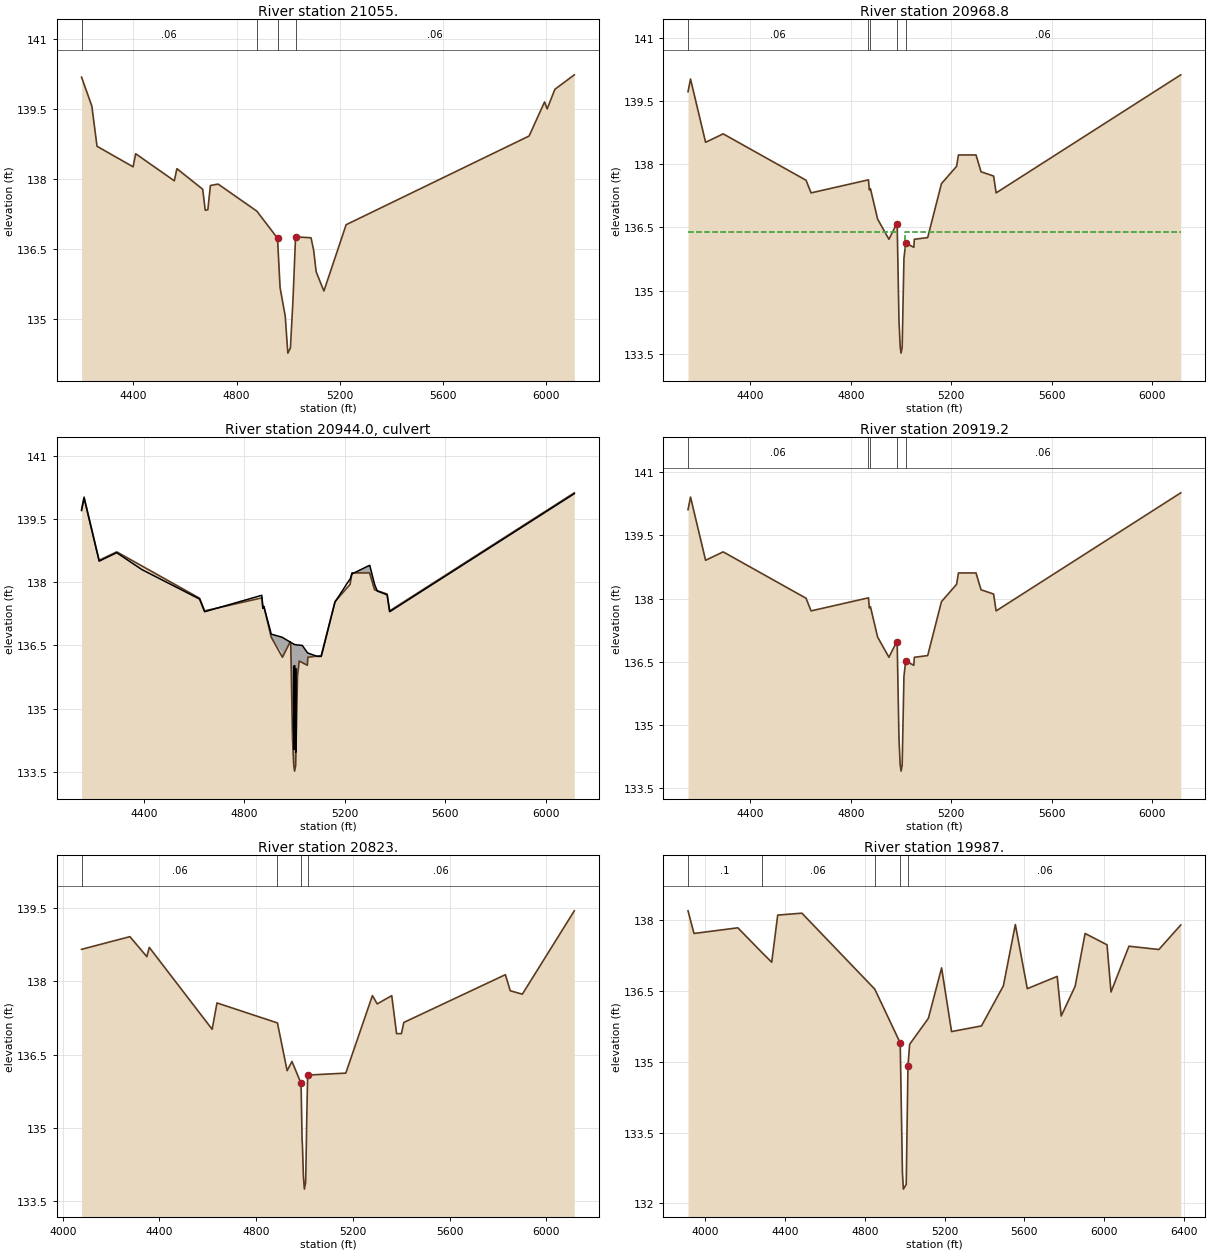
Type RM Length L Ch R = 1 ,21055.  ,86,86.2,86.3
BEGIN DESCRIPTION:
K131-00-00-S12_PRIVATE DR. 1_US-XS4
END DESCRIPTION:
XS GIS Cut Line= 4
      3067595.95      13946801.6      3066932.95     13946702.57
      3066589.06     13946795.62      3065847.59     13947279.41
#Sta/Elev= 30
  4198.5  140.18  4238.5  139.56  4258.5   138.7  4398.5  138.26  4408.5  138.54
  4558.5  137.96  4568.5  138.22  4668.5  137.78  4678.5  137.33  4688.5  137.34
  4698.5  137.86  4728.5  137.89  4878.9  137.31  4958.9  136.73  4968.9  135.67
  4988.9  135.06  4998.9  134.27  5008.9  134.38  5018.9  135.41  5028.9  136.76
  5088.9  136.74  5098.9  136.48  5108.9  136.01  5138.9   135.6  5225.1  137.02
  5935.1  138.92  5995.1  139.65  6005.1   139.5  6035.1  139.92  6110.5  140.23
#Mann= 4 ,-1 , 0
  4198.5     .06       0  4878.9    .055       0  4958.9    .045       0
  5028.9     .06       0
Bank Sta=4958.9,5028.9
Exp/Cntr=0.5,0.3

Type RM Length L Ch R = 1 ,20968.8 ,41.7,49.6,50
BEGIN DESCRIPTION:
Upstream Section of Bridge/Culvert/Weir
END DESCRIPTION:
XS GIS Cut Line= 4
      3067587.97     13946782.31      3066885.57     13946621.62
      3066541.68     13946714.68      3065800.21     13947198.46
#Sta/Elev= 30
  4151.5  139.72  4161.5  140.02  4221.5  138.52  4291.5  138.72  4621.5  137.62
  4641.5  137.32  4870.1  137.63  4873.4  137.39  4877.9  137.42  4906.4   136.7
  4951.5  136.22  4982.6  136.59  4984.6   136.5  4991.5   134.3  4996.3  133.67
  4999.8  133.52  5004.2  133.66  5011.3  135.77  5018.3  136.13  5050.7  136.03
  5052.6  136.22  5105.8  136.26  5160.7  137.54  5220.9  137.95  5228.3  138.22
  5298.3  138.22  5318.3  137.82  5368.3  137.72  5378.3  137.32  6113.6  140.12
#Mann= 5 ,-1 , 0
  4151.5     .06       0  4870.1    .045       0  4877.9    .055       0
  4982.6    .045       0  5018.3     .06       0
#XS Ineff= 2 , 0
       0  4985.1   136.4  5015.5       0   136.4
Permanent Ineff=
       F       F
Bank Sta=4982.6,5018.3
Exp/Cntr=0.5,0.3

Type RM Length L Ch R = 2 ,20944.0 ,,,
BEGIN DESCRIPTION:
PRIVATE DR. 1970' US SPRING CYPRESS
Need picture of S12
Structure ID: K131-00-00-S12
END DESCRIPTION:
Bridge Culvert--1,0,-1,-1, 0
Deck Dist Width WeirC Skew NumUp NumDn MinLoCord MaxHiCord MaxSubmerge Is_Ogee
10,31,2.6,0, 52, 52, , , 0.95, 0, ,,,
  4151.5  4161.5  4221.5  4291.5  4391.5  4506.5  4621.5  4641.5  4793.3  4863.3
  4869.2  4870.1  4873.4    4877  4877.9  4880.6    4897  4903.4  4906.4  4947.3
  4948.7  4951.5  4982.6  4984.6  4991.5  4995.2  4996.3  4999.8  5000.1  5004.2
  5004.9  5011.3  5018.3  5030.6  5050.7  5052.6  5090.6  5105.8  5109.4  5160.7
  5217.5  5220.9  5228.3  5229.1  5298.3  5299.1  5318.3  5329.1  5329.2  5368.3
  5378.3  6113.6
   139.7     140   138.5   138.7   138.3  137.95   137.6   137.3  137.56  137.68
  137.69  137.62  137.38  137.43  137.41  137.35  136.99  136.85  136.77   136.7
   136.7  136.69  136.58  136.57  136.55  136.54  136.53  136.52  136.52  136.52
  136.52  136.51  136.51   136.5  136.33  136.32  136.24  136.24  136.32  137.53
  138.05  138.07  138.21   138.2   138.4   138.4  137.95  137.79  137.79   137.7
   137.3   140.1
   139.7     140   138.5   138.7   138.3  137.95   137.6   137.3  137.55  137.67
  137.68  137.61  137.37  137.42   137.4  137.34  136.98  136.84  136.68  136.34
  136.29   136.2  136.57  136.48  134.28  133.85  133.65   133.5  133.51  133.64
  133.86  135.75  136.11  136.07  136.01   136.2  136.23  136.24  136.31  137.52
  138.04  137.93   138.2   138.2   138.2  138.18   137.8  137.78  137.78   137.7
   137.3   140.1
  4151.5  4161.5  4221.5  4291.5  4391.5  4506.5  4621.5  4641.5  4793.3  4863.3
  4869.2  4870.1  4873.4    4877  4877.9  4880.6    4897  4903.4  4906.4  4947.3
  4948.7  4951.5  4982.6  4984.6  4991.5  4995.2  4996.3  4999.8  5000.1  5004.2
  5004.9  5011.3  5018.3  5030.6  5050.7  5052.6  5090.6  5105.8  5109.4  5160.7
  5217.5  5220.9  5228.3  5229.1  5298.3  5299.1  5318.3  5329.1  5329.2  5368.3
  5378.3  6113.6
   139.7     140   138.5   138.7   138.3  137.95   137.6   137.3  137.56  137.68
  137.69  137.62  137.38  137.43  137.41  137.35  136.99  136.85  136.77   136.7
   136.7  136.69  136.58  136.57  136.55  136.54  136.53  136.52  136.52  136.52
  136.52  136.51  136.51   136.5  136.33  136.32  136.24  136.24  136.32  137.53
  138.05  138.07  138.21   138.2   138.4   138.4  137.95  137.79  137.79   137.7
   137.3   140.1
   139.7     140   138.5   138.7   138.3  137.95   137.6   137.3  137.55  137.67
  137.68  137.61  137.37  137.42   137.4  137.34  136.98  136.84  136.68  136.34
  136.29   136.2  136.57  136.48  134.28  133.85  133.65   133.5  133.51  133.64
  133.86  135.75  136.11  136.07  136.01   136.2  136.23  136.24  136.31  137.52
  138.04  137.93   138.2   138.2   138.2  138.18   137.8  137.78  137.78   137.7
   137.3   140.1
BR Coef= 1 , 1 , 0 ,1.25, 0 ,,,0.8,0,2,0,
WSPro=,,,, 1 ,,,, 0 ,,,, 0 ,,,,-1 ,-1 ,-1 , 0 , 0 , 0 , 0 , 0
Culvert=1,2,,31,0.015,0.4,1,1,1,134.02,4996.1,133.83,4996.1,Culvert #1  , 0 ,10
Culvert Bottom n=0.015
Culvert=1,2,,31,0.015,0.4,1,1,3,134.03,4999.9,133.61,4999.9,Culvert #2  , 0 ,10
Culvert Bottom n=0.015
Culvert=1,2,,31,0.015,0.4,1,1,3,133.96,5004.5,133.46,5004.5,Culvert #3  , 0 ,10
Culvert Bottom n=0.015
BR D #Sta/Elev= 52
  4151.5  139.72  4161.5  140.02  4221.5  138.52  4291.5  138.72  4391.5  138.32
  4506.5  137.97  4621.5  137.62  4641.5  137.32  4793.3  137.57  4863.3  137.69
  4869.2   137.7  4870.1  137.63  4873.4  137.39    4877  137.44  4877.9  137.42
  4880.6  137.36    4897     137  4903.4  136.86  4906.4   136.7  4947.3  136.36
  4948.7  136.31  4951.5  136.22  4982.6  136.59  4984.6   136.5  4991.5   134.3
  4995.2  133.87  4996.3  133.67  4999.8  133.52  5000.1  133.53  5004.2  133.66
  5004.9  133.88  5011.3  135.77  5018.3  136.13  5030.6  136.09  5050.7  136.03
  5052.6  136.22  5090.6  136.25  5105.8  136.26  5109.4  136.33  5160.7  137.54
  5217.5  138.06  5220.9  137.95  5228.3  138.22  5229.1  138.22  5298.3  138.22
  5299.1   138.2  5318.3  137.82  5329.1   137.8  5329.2   137.8  5368.3  137.72
  5378.3  137.32  6113.6  140.12
BR D #Mann= 5
  4151.5     .06  4870.1    .045  4877.9    .055  4982.6    .045  5018.3     .06
BC Design=,, 0 ,, 0 ,,,,,,
BC HTab HWMax=140.12

Type RM Length L Ch R = 1 ,20919.2 ,44.1,96.2,97
BEGIN DESCRIPTION:
Downstream Section of Bridge/Culvert/Weir
END DESCRIPTION:
XS GIS Cut Line= 4
      3067583.16      13946739.4      3066885.16     13946579.79
       3066533.4     13946674.97      3065795.05      13947156.7
#Sta/Elev= 30
  4151.5  140.11  4161.5  140.41  4221.5  138.91  4291.5  139.11  4621.5  138.01
  4641.5  137.71  4870.1  138.02  4873.4  137.78  4877.9  137.81  4906.4  137.09
  4951.5  136.61  4982.6  136.98  4984.6  136.89  4991.5  134.69  4996.3  134.06
  4999.8  133.91  5004.2  134.05  5011.3  136.16  5018.3  136.52  5050.7  136.42
  5052.6  136.61  5105.8  136.65  5160.7  137.93  5220.9  138.34  5228.3  138.61
  5298.3  138.61  5318.3  138.21  5368.3  138.11  5378.3  137.71  6113.6  140.51
#Mann= 5 ,-1 , 0
  4151.5     .06       0  4870.1    .045       0  4877.9    .055       0
  4982.6    .045       0  5018.3     .06       0
#XS Ineff= 2 , 0
       0  4985.1  135.65  5015.5       0  135.45
Permanent Ineff=
       F       F
Bank Sta=4982.6,5018.3
Exp/Cntr=0.5,0.3

Type RM Length L Ch R = 1 ,20823.  ,834.1,836,893.2
BEGIN DESCRIPTION:
K131-00-00-S12_PRIVATE DR. 1_DS - XS 1
END DESCRIPTION:
XS GIS Cut Line= 4
       3067659.7      13946717.9      3066793.31     13946515.13
      3066730.77     13946520.09      3065791.83     13947063.68
#Sta/Elev= 29
  4077.8  138.66  4277.8  138.92  4347.8  138.51  4357.8   138.7  4617.8  137.02
  4637.8  137.56  4887.8  137.15  4927.8  136.17  4947.8  136.36 4985.42  135.91
 4989.69  134.78 4991.46   134.6 4995.16     134 4999.15  133.74 5004.34  133.88
 5005.92  134.27 5009.07  135.21 5012.71  136.08  5170.4  136.12  5280.4  137.71
  5300.4  137.54  5360.4  137.71  5380.4  136.93  5400.4  136.93  5410.4  137.16
  5830.4  138.14  5850.4  137.81  5900.4  137.74  6115.3  139.45
#Mann= 4 ,-1 , 0
  4077.8     .06       0  4887.8    .055       0 4985.42    .045       0
 5012.71     .06       0
Bank Sta=4985.42,5012.71
Exp/Cntr=0.3,0.1

Type RM Length L Ch R = 1 ,19987.  ,47.4,99.9,152.4
BEGIN DESCRIPTION:
K131-00-00-S09_SPRING CYPRESS RD_US - XS 4
END DESCRIPTION:
XS GIS Cut Line= 5
       3067946.8       13946185.      3067447.56     13945907.11
      3067080.46     13945737.45      3066804.14     13945728.53
      3065734.56     13945141.79
#Sta/Elev= 30
    3913   138.2    3943  137.72    4163  137.84    4283  137.32    4333  137.11
    4363  138.11  4484.4  138.15    4850  136.54 4977.65   135.4 4988.77  132.65
 4993.48   132.3  5007.8   132.4 5016.51  134.91 5024.97  135.37  5118.8  135.92
  5185.3  136.99  5235.3  135.64  5385.3  135.76  5495.3  136.61  5555.3  137.91
  5615.3  136.55  5765.3  136.81  5785.3  135.97  5855.3   136.6  5905.3  137.72
  6015.3  137.48  6035.3  136.48  6125.3  137.45  6275.3  137.38  6385.3   137.9
#Mann= 5 ,-1 , 0
    3913      .1       0    4283     .06       0    4850     .12       0
 4977.65    .055       0 5016.51     .06       0
#XS Ineff= 2 , 0
       0                    5187       0  136.85
Permanent Ineff=
       F       F
Bank Sta=4977.65,5016.51
Exp/Cntr=0.5,0.3

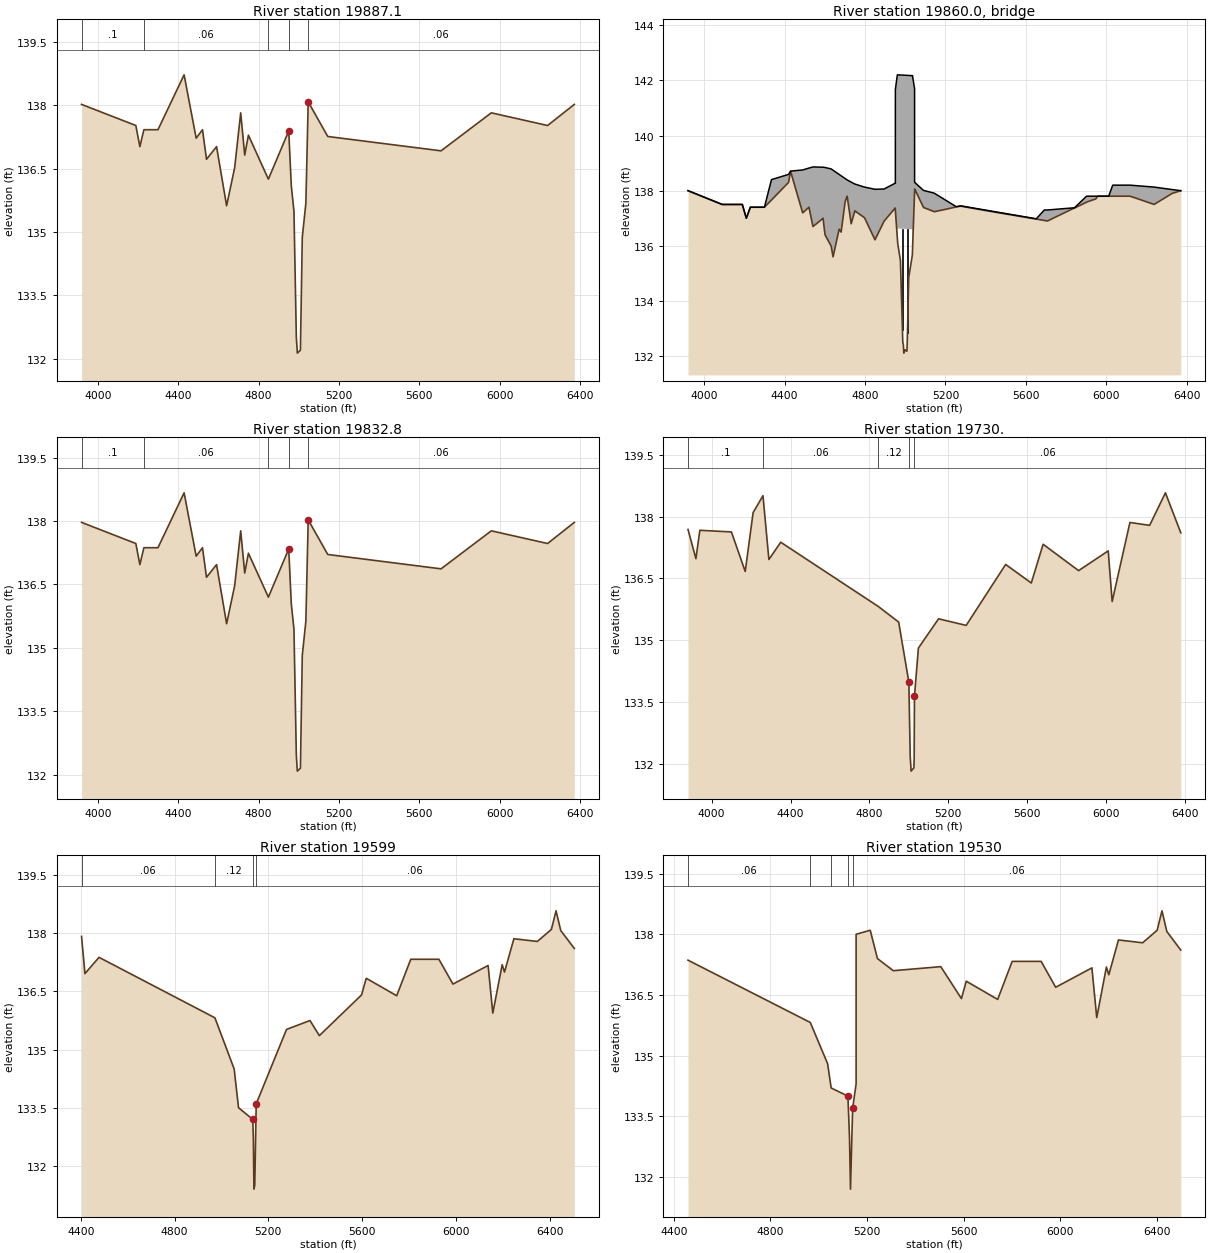
Type RM Length L Ch R = 1 ,19887.1 ,60.1,54.3,53
BEGIN DESCRIPTION:
Upstream Section of Bridge/Culvert/Weir
END DESCRIPTION:
XS GIS Cut Line= 5
      3067936.61     13946088.33      3067437.37     13945810.31
      3067187.46     13945737.51      3066718.15     13945523.08
      3065724.37     13945044.99
#Sta/Elev= 30
  3919.7  138.02  4189.7  137.52  4209.7  137.02  4229.7  137.42  4299.7  137.42
  4429.7  138.72  4489.7  137.22  4521.1  137.42  4541.1  136.72  4591.1  137.02
  4641.1  135.62  4681.1  136.52  4711.1  137.82  4731.1  136.82  4749.5  137.29
  4848.8  136.25    4950  137.39  4962.8  136.09    4976  135.49  4987.8  132.51
  4992.8  132.13  5008.1   132.2  5017.4  134.87  5035.2  135.68  5046.9  138.08
  5144.1  137.26  5707.4  136.92  5957.4  137.82  6237.4  137.52  6370.2  138.02
#Mann= 5 ,-1 , 0
  3919.7      .1       0  4229.7     .06       0  4848.8     .12       0
    4950    .055       0  5046.9     .06       0
#XS Ineff= 2 , 0
       0  4943.5     137 5051.75       0     137
Permanent Ineff=
       F       F
Bank Sta=4950,5046.9
Exp/Cntr=0.5,0.3

Type RM Length L Ch R = 3 ,19860.0 ,,,
BEGIN DESCRIPTION:
SPRING CYPRESS RD.
Structure ID: K131-00-00-S09
END DESCRIPTION:
Bridge Culvert--1,0,-1,-1, 0
Deck Dist Width WeirC Skew NumUp NumDn MinLoCord MaxHiCord MaxSubmerge Is_Ogee
10,36,2.6,0, 54, 54, , , 0.95, 0, ,,,
  3919.7  4089.7  4189.7  4209.7  4229.7  4299.7  4334.7  4419.7  4429.7  4489.7
  4521.1  4541.1  4591.1  4601.1  4631.1  4641.1  4671.1  4681.1  4701.1  4711.1
  4731.1  4749.5  4797.1  4849.6  4894.4    4950 4950.79  4950.9 4960.49 4960.99
  4961.1    5036 5036.09 5036.19  5046.4 5046.51  5046.9  5090.7  5144.1  5253.4
  5275.6  5651.7  5691.7  5707.4  5841.7  5901.7  5947.4  5957.4  6011.7  6031.7
  6117.4  6237.4  6327.4  6370.2
     138   137.5   137.5     137   137.4   137.4   138.4  138.59  138.71  138.75
  138.82  138.86  138.85  138.84  138.79  138.74  138.59  138.54  138.44  138.39
  138.31  138.24  138.13  138.05  138.06  138.27  138.27  141.67  142.19   142.2
   142.2  142.17  142.16  142.16   141.7   138.3   138.3  138.01  137.91  137.42
  137.45  136.98   137.3   137.3  137.38   137.8   137.8   137.8   137.8   138.2
   138.2  138.13  138.04     138
     138   137.5   137.5     137   137.4   137.4  137.66   138.3   138.7   137.2
   137.4   136.7     137   136.4     136   135.6   136.6   136.5   137.6   137.8
   136.8  137.27  137.02  136.22  136.89  137.37  137.29  137.28   136.3  136.25
  136.63   136.6  136.59  135.86  137.96  137.98  138.06  137.39  137.24  137.41
  137.44  136.97  136.92   136.9  137.37  137.58   137.7   137.8   137.8   137.8
   137.8   137.5   137.9     138
  3919.7  4089.7  4189.7  4209.7  4229.7  4299.7  4334.7  4419.7  4429.7  4489.7
  4521.1  4541.1  4591.1  4601.1  4631.1  4641.1  4671.1  4681.1  4701.1  4711.1
  4731.1  4749.5  4797.1  4849.6  4894.4    4950 4950.79  4950.9 4960.49 4960.99
  4961.1    5036 5036.09 5036.19  5046.4 5046.51  5046.9  5090.7  5144.1  5253.4
  5275.6  5651.7  5691.7  5707.4  5841.7  5901.7  5947.4  5957.4  6011.7  6031.7
  6117.4  6237.4  6327.4  6370.2
     138   137.5   137.5     137   137.4   137.4   138.4  138.59  138.71  138.75
  138.82  138.86  138.85  138.84  138.79  138.74  138.59  138.54  138.44  138.39
  138.31  138.24  138.13  138.05  138.06  138.27  138.27  141.67  142.19   142.2
   142.2  142.17  142.16  142.16   141.7   138.3   138.3  138.01  137.91  137.42
  137.45  136.98   137.3   137.3  137.38   137.8   137.8   137.8   137.8   138.2
   138.2  138.13  138.04     138
     138   137.5   137.5     137   137.4   137.4  137.66   138.3   138.7   137.2
   137.4   136.7     137   136.4     136   135.6   136.6   136.5   137.6   137.8
   136.8  137.27  137.02  136.22  136.89  137.37  137.29  137.28   136.3  136.25
  136.63   136.6  136.59  135.86  137.96  137.98  138.06  137.39  137.24  137.41
  137.44  136.97  136.92   136.9  137.37  137.58   137.7   137.8   137.8   137.8
   137.8   137.5   137.9     138
Pier Skew, UpSta & Num, DnSta & Num=  ,4986, 2 ,4986, 2 , 0 , 0 , 0 ,,
     1.3     1.3
  131.78  137.62
     1.3     1.3
  131.78  137.62
Pier Skew, UpSta & Num, DnSta & Num=  ,5010.9, 2 ,5010.9, 2 , 0 , 0 , 0 ,,
     1.3     1.3
  131.63  137.61
     1.3     1.3
  131.63  137.61
BR Coef= 1 , 1 , 1 ,1.25, 0 ,,,0.8,0,2,0,
WSPro=,,,, 1 ,,,, 0 ,,,, 0 ,,,,-1 ,-1 ,-1 , 0 , 0 , 0 , 0 , 0
BR U #Sta/Elev= 97
  3919.7     138  4089.7   137.5  4189.7   137.5  4209.7     137  4229.7   137.4
  4299.7   137.4  4334.7  137.66  4419.7   138.3  4429.7   138.7  4489.7   137.2
  4491.1   137.2  4521.1   137.4  4541.1   136.7  4558.6   136.8  4591.1     137
  4601.1   136.4  4628.6  136.03  4631.1     136  4641.1   135.6  4671.1   136.6
  4681.1   136.5  4701.1   137.6  4708.6  137.75  4711.1   137.8  4731.1   136.8
  4749.5  137.27  4750.7  137.26  4797.1  137.02    4798  137.01  4848.8  136.23
  4849.6  136.22  4893.9  136.88  4894.4  136.89    4950  137.37 4950.79  137.29
  4950.9  137.28 4951.01  137.27 4960.49   136.3  4960.6  136.29 4960.71  136.28
 4960.81  136.27  4960.9  136.26 4960.99  136.25  4961.1  136.24  4961.2  136.23
 4961.31  136.22  4962.8  136.07    4976  135.47  4987.8  132.49  4990.5  132.44
  4992.8  132.11  4999.4  132.23  5008.1  132.18  5009.6  132.43  5017.4  134.85
  5035.2  135.66 5035.69  135.76  5035.8  135.78 5035.91  135.81    5036  135.82
 5036.09  135.84 5036.19  135.86  5036.3  135.89  5036.4  135.91 5036.51  135.93
 5046.29  137.93  5046.4  137.96 5046.51  137.98  5046.9  138.06  5090.2   137.4
  5090.7  137.39  5144.1  137.24  5146.1  137.24  5198.6  137.32  5253.4  137.41
  5275.6  137.44  5321.7  137.38  5431.7  137.24  5651.7  136.97  5691.7  136.92
  5707.4   136.9  5831.7  137.34  5841.7  137.37  5901.7  137.58  5907.4   137.6
  5947.4   137.7  5957.4   137.8  6011.7   137.8  6031.7   137.8  6083.4   137.8
  6102.2   137.8  6117.4   137.8  6158.6   137.7  6237.4   137.5  6327.4   137.9
 6370.15     138  6370.2     138
BR U #Mann= 5
  3919.7      .1  4229.7     .06  4849.6     .12    4950    .055  5046.9     .06
BR D #Sta/Elev= 97
  3919.7     138  4089.7   137.5  4189.7   137.5  4209.7     137  4229.7   137.4
  4299.7   137.4  4334.7  137.66  4419.7   138.3  4429.7   138.7  4489.7   137.2
  4491.1   137.2  4521.1   137.4  4541.1   136.7  4558.6   136.8  4591.1     137
  4601.1   136.4  4628.6  136.03  4631.1     136  4641.1   135.6  4671.1   136.6
  4681.1   136.5  4701.1   137.6  4708.6  137.75  4711.1   137.8  4731.1   136.8
  4749.5  137.27  4750.7  137.26  4797.1  137.02    4798  137.01  4848.8  136.23
  4849.6  136.22  4893.9  136.88  4894.4  136.89    4950  137.37 4950.79  137.29
  4950.9  137.28 4951.01  137.27 4960.49   136.3  4960.6  136.29 4960.71  136.28
 4960.81  136.27  4960.9  136.26 4960.99  136.25  4961.1  136.24  4961.2  136.23
 4961.31  136.22  4962.8  136.07    4976  135.47  4987.8  132.49  4990.5  132.44
  4992.8  132.11  4999.4  132.23  5008.1  132.18  5009.6  132.43  5017.4  134.85
  5035.2  135.66 5035.69  135.76  5035.8  135.78 5035.91  135.81    5036  135.82
 5036.09  135.84 5036.19  135.86  5036.3  135.89  5036.4  135.91 5036.51  135.93
 5046.29  137.93  5046.4  137.96 5046.51  137.98  5046.9  138.06  5090.2   137.4
  5090.7  137.39  5144.1  137.24  5146.1  137.24  5198.6  137.32  5253.4  137.41
  5275.6  137.44  5321.7  137.38  5431.7  137.24  5651.7  136.97  5691.7  136.92
  5707.4   136.9  5831.7  137.34  5841.7  137.37  5901.7  137.58  5907.4   137.6
  5947.4   137.7  5957.4   137.8  6011.7   137.8  6031.7   137.8  6083.4   137.8
  6102.2   137.8  6117.4   137.8  6158.6   137.7  6237.4   137.5  6327.4   137.9
 6370.15     138  6370.2     138
BR D #Mann= 5
  3919.7      .1  4229.7     .06  4849.6     .12    4950    .055  5046.9     .06
BC Design=,, 0 ,, 0 ,,,,,,
BC HTab HWMax=138.72

Type RM Length L Ch R = 1 ,19832.8 ,143.3,102.8,55.4
BEGIN DESCRIPTION:
Downstream Section of Bridge/Culvert/Weir
END DESCRIPTION:
XS GIS Cut Line= 5
      3067952.75     13946033.85      3067451.53     13945754.73
      3067200.85      13945681.7      3066733.05     13945467.97
      3065739.45     13944989.96
#Sta/Elev= 30
  3919.7  137.97  4189.7  137.47  4209.7  136.97  4229.7  137.37  4299.7  137.37
  4429.7  138.67  4489.7  137.17  4521.1  137.37  4541.1  136.67  4591.1  136.97
  4641.1  135.57  4681.1  136.47  4711.1  137.77  4731.1  136.77  4749.5  137.24
  4848.8   136.2    4950  137.34  4962.8  136.04    4976  135.44  4987.8  132.46
  4992.8  132.08  5008.1  132.15  5017.4  134.82  5035.2  135.63  5046.9  138.03
  5144.1  137.21  5707.4  136.87  5957.4  137.77  6237.4  137.47  6370.2  137.97
#Mann= 5 ,-1 , 0
  3919.7      .1       0  4229.7     .06       0  4848.8     .12       0
    4950    .055       0  5046.9     .06       0
#XS Ineff= 2 , 0
       0  4948.4   136.5  5049.5       0   136.5
Permanent Ineff=
       F       F
Bank Sta=4950,5046.9
Exp/Cntr=0.5,0.3

Type RM Length L Ch R = 1 ,19730.  ,128,129,123
BEGIN DESCRIPTION:
K131-00-00-S09_SPRING CYPRESS RD_DS - XS 1
END DESCRIPTION:
XS GIS Cut Line= 4
       3067953.5       13945980.      3067260.52     13945509.25
      3066830.88      13945462.9      3065744.54     13944890.62
#Sta/Elev= 30
  3880.5  137.69  3920.5  136.98  3940.5  137.67  4100.5  137.63  4170.5  136.67
  4210.5   138.1  4260.5  138.51  4290.5  136.96  4350.5  137.38    4845  135.82
  4948.4  135.44    5000  133.98 5006.77  132.18 5011.42  131.82 5025.53   131.9
 5026.92  132.13  5028.4  133.64  5048.4  134.81  5150.6  135.52  5290.6  135.36
  5490.6  136.84  5620.6  136.39  5680.6  137.33  5860.6  136.69  6010.6  137.17
  6030.6  135.94  6120.6  137.86  6220.6  137.79  6300.6  138.58  6378.4  137.61
#Mann= 5 ,-1 , 0
  3880.5      .1       0  4260.5     .06       0    4845     .12       0
    5000    .055       0  5028.4     .06       0
Bank Sta=5000,5028.4
Exp/Cntr=0.3,0.1

Type RM Length L Ch R = 1 ,19599   ,68,69,78
BEGIN DESCRIPTION:
As-Built Channel Survey - Overbank Copied From 19730
END DESCRIPTION:
XS GIS Cut Line= 5
  3067541.60629913945564.7503435      3067268.49      13945380.9
      3066848.46     13945336.42        3066093.      13944927.7
 3065981.2997475 13944867.267777
#Sta/Elev= 30
    4403  137.92  4417.5  136.96  4477.5  137.38    4972  135.82 5054.12   134.5
  5072.8   133.5 5133.47   133.2 5136.09   132.7 5138.42   131.4 5142.11   131.5
 5148.15   133.6  5277.6  135.52  5377.6  135.75  5417.6  135.36  5597.6  136.41
  5617.6  136.84  5747.6  136.39  5807.6  137.33  5927.6  137.33  5987.6  136.69
  6137.6  137.17  6157.6  135.94  6197.6  137.19  6207.6     137  6247.6  137.86
  6347.6  137.79  6407.6   138.1  6427.6  138.58  6447.6  138.07  6505.4  137.61
#Mann= 4 ,-1 , 0
    4403     .06       0    4972     .12       0 5133.47    .045       0
 5148.15     .06       0
Bank Sta=5133.47,5148.15
Exp/Cntr=0.3,0.1

Type RM Length L Ch R = 1 ,19530   ,198,241,283
BEGIN DESCRIPTION:
As-Built Channel Survey - Overbank Copied From 19730
END DESCRIPTION:
XS GIS Cut Line= 6
  3067510.01314413945466.4079872  3067490.32918313945453.2088293
 3067488.668068813945452.0949624      3067282.98     13945314.17
      3066862.96     13945269.69  3066001.95703913944803.8576062
#Sta/Elev= 30
 4458.97  137.36    4965  135.82 5036.77   134.8 5051.43   134.2 5120.75     134
 5127.21     133 5131.42   131.7 5140.29   133.7 5154.67   134.3 5154.68     138
 5213.07   138.1 5242.97   137.4 5308.67   137.1 5505.07   137.2  5590.6  136.41
  5610.6  136.84  5740.6  136.39  5800.6  137.33  5920.6  137.33  5980.6  136.69
  6130.6  137.17  6150.6  135.94  6190.6  137.19  6200.6     137  6240.6  137.86
  6340.6  137.79  6400.6   138.1  6420.6  138.58  6440.6  138.07  6498.4  137.61
#Mann= 5 ,-1 , 0
 4458.97     .06       0    4965     .12       0 5051.43     .06       0
 5120.75    .045       0 5140.29     .06       0
#Block Obstruct= 2 , 0
       0                  6140.6       0  136.37
Bank Sta=5120.75,5140.29
Exp/Cntr=0.3,0.1

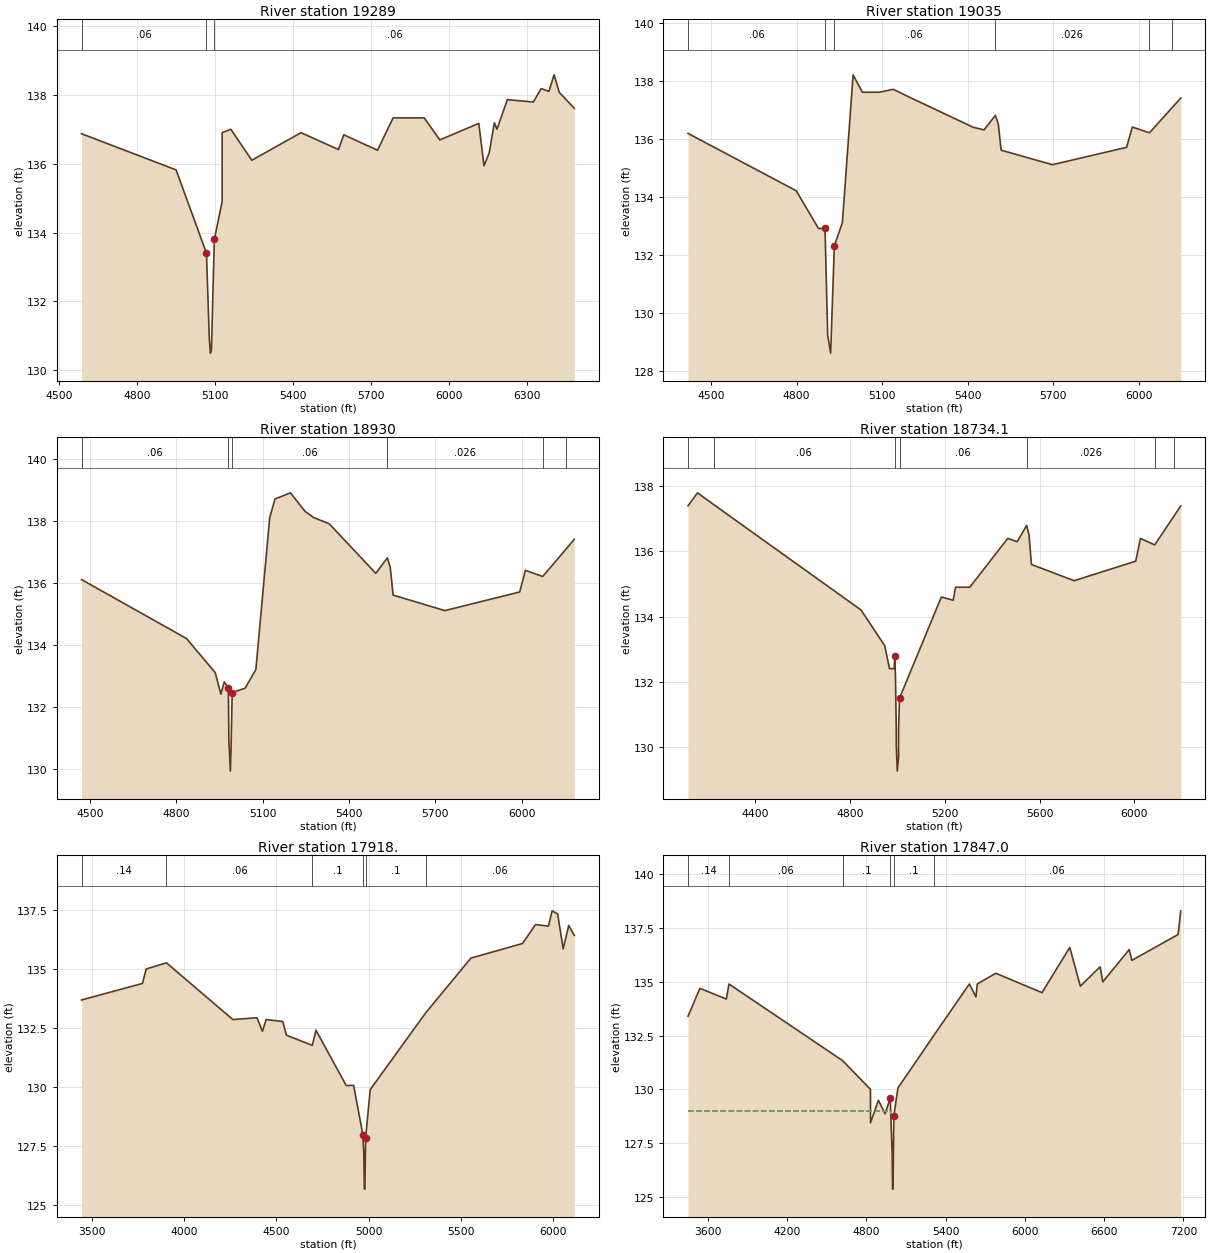
Type RM Length L Ch R = 1 ,19289   ,177,264,293
BEGIN DESCRIPTION:
As-Built Channel Survey - Overbank Copied From 19730
END DESCRIPTION:
XS GIS Cut Line= 6
  3067469.44751913945298.2566038      3067275.85     13945129.43
        3066984.     13945022.46      3066228.54     13944613.74
 3066140.850732313944566.2982328  3066137.06892713944564.2521954
#Sta/Elev= 30
    4585  136.87    4949  135.82 5066.09   133.4 5076.99   130.9 5081.25   130.5
 5085.12   130.6 5096.23   133.8 5126.43   134.9 5126.44   136.9 5159.69     137
 5240.59   136.1 5430.15   136.9  5574.6  136.41  5594.6  136.84  5724.6  136.39
  5784.6  137.33  5904.6  137.33  5964.6  136.69  6114.6  137.17  6134.6  135.94
  6154.6  136.31  6174.6  137.19  6184.6     137  6224.6  137.86  6324.6  137.79
  6354.6  138.18  6384.6   138.1  6404.6  138.58  6424.6  138.07  6482.4  137.61
#Mann= 3 ,-1 , 0
    4585     .06       0 5066.09    .045       0 5096.23     .06       0
Bank Sta=5066.09,5096.23
Exp/Cntr=0.3,0.1

Type RM Length L Ch R = 1 ,19035   ,72,73,73
BEGIN DESCRIPTION:
Used As-Built Channel Survey - Overbank Copied from 18734.1
END DESCRIPTION:
XS GIS Cut Line= 4
      3067557.56     13945354.02      3067343.94     13944913.99
      3067290.93     13944831.13        3066399.     13944099.49
#Sta/Elev= 28
    4419  136.18    4534  135.58  4798.7   134.2 4876.63   132.9  4899.5   132.9
 4908.96   129.2 4914.22   128.9 4919.22   128.6  4932.2   132.3  4960.4   133.1
 4998.05   138.2 5030.35   137.6 5089.92   137.6 5138.73   137.7  5201.8   137.4
  5417.3   136.4  5419.6  136.39  5457.3   136.3  5488.2  136.69  5497.3   136.8
  5507.3   136.5  5517.3   135.6  5697.3   135.1  5957.3   135.7  5977.3   136.4
  6037.3   136.2  6117.2  137.07  6147.3   137.4
#Mann= 6 ,-1 , 0
    4419     .06       0  4899.5    .045       0  4932.2     .06       0
  5497.3    .026       0  6037.3     .06       0  6117.2     .14       0
#Block Obstruct= 2 , 0
       0                    5270       0   136.4
Bank Sta=4899.5,4932.2
Exp/Cntr=0.3,0.1

Type RM Length L Ch R = 1 ,18930   ,158,196,205
BEGIN DESCRIPTION:
Used As-Built Channel Survey - Overbank Copied from 18734.1
END DESCRIPTION:
XS GIS Cut Line= 5
  3067621.96081113945394.2004826      3067617.33     13945383.13
       3067432.8     13944941.99      3067379.79     13944859.13
 3066497.137900513944135.1005559
#Sta/Elev= 30
    4470   136.1    4570  135.58  4834.7   134.2  4934.7   133.1  4954.5   132.4
 4966.07   132.8 4980.36   132.6 4982.28   130.9  4987.4  129.92 4989.74   130.6
  4993.7  132.45  5039.2   132.6  5076.1   133.2  5124.2   138.1  5142.6   138.7
  5196.3   138.9  5247.2   138.3  5277.6   138.1  5331.2   137.9  5493.3   136.3
  5524.2  136.69  5533.3   136.8  5543.3   136.5  5553.3   135.6  5733.3   135.1
  5993.3   135.7  6013.3   136.4  6073.3   136.2  6153.2  137.07  6183.3   137.4
#Mann= 6 ,-1 , 0
    4470     .06       0 4980.36    .055       0  4993.7     .06       0
  5533.3    .026       0  6073.3     .06       0  6153.2     .14       0
#Block Obstruct= 2 , 0
       0                    5380       0   136.8
Bank Sta=4980.36,4993.7
Exp/Cntr=0.3,0.1

Type RM Length L Ch R = 1 ,18734.1 ,879.8,816.1,815.3
BEGIN DESCRIPTION:
Cross Section K131-00-00-X05A; Blocked obstruction on right is detention pond VRR
END DESCRIPTION:
XS GIS Cut Line= 4
      3067684.96       13945727.      3067612.97      13944880.3
      3067556.33     13944799.38      3066683.62      13944081.5
#Sta/Elev= 30
  4116.7   137.4  4156.7   137.8  4224.8  137.44  4846.7   134.2  4946.7   133.1
  4966.5   132.4  4986.5   132.4  4988.6   132.8  4991.7  132.18  4995.1  130.58
  4995.4  130.02  4999.4  129.25  5004.8  129.68 5004.91  130.53  5008.8  131.49
  5185.3   134.6  5235.3   134.5  5245.3   134.9  5305.3   134.9  5465.3   136.4
  5505.3   136.3  5545.3   136.8  5555.3   136.5  5565.3   135.6  5745.3   135.1
  6005.3   135.7  6025.3   136.4  6085.3   136.2  6165.2  137.07  6195.3   137.4
#Mann= 7 ,-1 , 0
  4116.7      .1       0  4224.8     .06       0  4988.6    .055       0
  5008.8     .06       0  5545.3    .026       0  6085.3     .06       0
  6165.2     .14       0
#Block Obstruct= 2 , 0
       0                  5545.3       0   136.4
Bank Sta=4988.6,5008.8
Exp/Cntr=0.3,0.1

Type RM Length L Ch R = 1 ,17918.  ,70,71,87.4
BEGIN DESCRIPTION:
K131-00-00-S08_KLIEN CEMETERY RD_US - XS 4
END DESCRIPTION:
XS GIS Cut Line= 4
      3068697.38       13945721.       3068256.8     13944357.08
      3068001.92     13944154.79      3067104.82      13944000.9
#Sta/Elev= 30
  3445.2  133.68  3775.2  134.38  3795.2  134.99  3905.2  135.25  4265.2  132.85
  4395.2  132.93  4425.2  132.36  4445.2  132.85  4535.2  132.77  4555.2  132.19
  4695.2  131.76  4715.2   132.4  4879.1  130.06  4919.1  130.07  4969.1  127.99
 4974.22  127.19 4977.22  125.68 4979.88  125.68 4984.21  127.86  5009.1  129.89
    5310  133.14  5554.5  135.45  5834.5  136.07  5904.5  136.87  5974.5   136.8
  5994.5  137.45  6024.5  137.32  6054.5  135.84  6084.5  136.83  6114.7  136.41
#Mann= 6 ,-1 , 0
  3445.2     .14       0  3905.2     .06       0  4695.2      .1       0
  4969.1    .055       0 4984.21      .1       0    5310     .06       0
Bank Sta=4969.1,4984.21
Exp/Cntr=0.5,0.3

Type RM Length L Ch R = 1 ,17847.0 ,60,59.5,41.5
BEGIN DESCRIPTION:
Upstream Section of Bridge/Culvert/Weir
END DESCRIPTION:
XS GIS Cut Line= 4
      3068760.94     13945660.43      3068320.36     13944295.95
      3068065.48     13944093.66      3066309.53     13943200.06
#Sta/Elev= 30
  3450.9   133.4  3540.9   134.7  3740.9   134.2  3760.9   134.9  4620.9  131.34
  4831.2  130.01  4831.9     130 4832.01  128.45    4892   129.5  4942.9  128.87
  4981.2  129.61  4996.1  126.98  4999.2  125.37  5002.1  125.37  5008.9  128.79
  5039.8  130.07  5310.2   132.5  5580.2   134.9  5630.2   134.3  5640.2   134.9
  5780.2   135.4  6130.2   134.5  6340.2   136.6  6420.2   134.8  6570.2   135.7
  6590.2     135  6790.2   136.5  6810.2     136  7160.2   137.2  7180.4   138.3
#Mann= 6 ,-1 , 0
  3450.9     .14       0  3760.9     .06       0  4620.9      .1       0
  4981.2    .055       0  5008.9      .1       0  5310.2     .06       0
#XS Ineff= 2 , 0
       0 4985.45     129 5014.65       0     129
Permanent Ineff=
       F       F
Bank Sta=4981.2,5008.9
Exp/Cntr=0.5,0.3