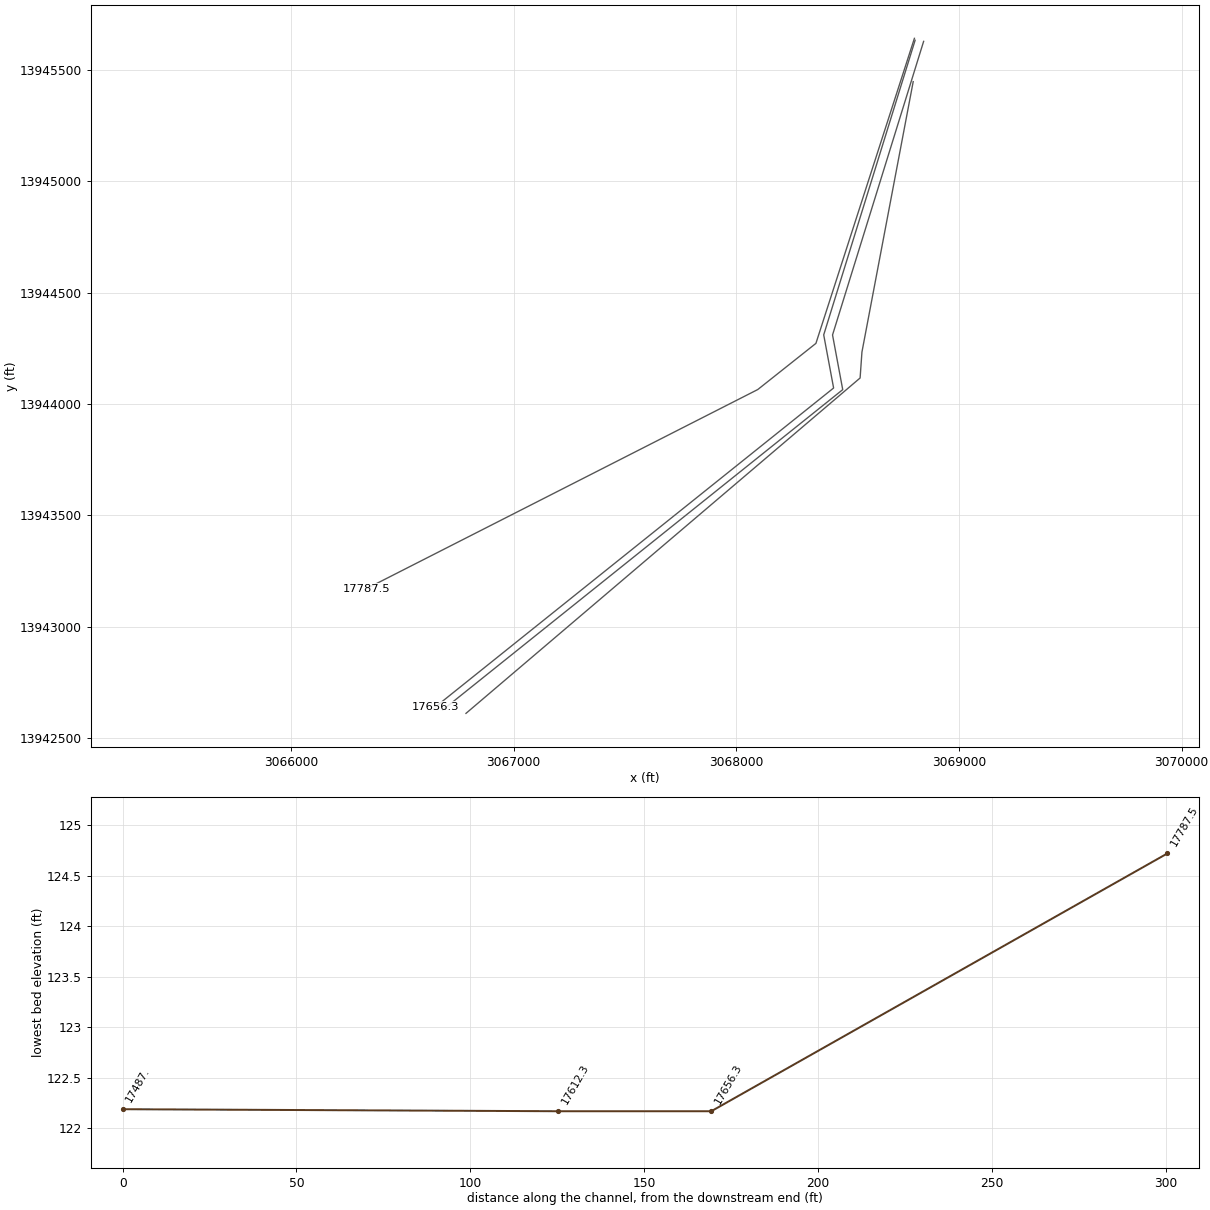
HEC-RAS study K131-00-00.prj: K131-00-00

--- K131-00-00.g04 (geometry) --- (continued)

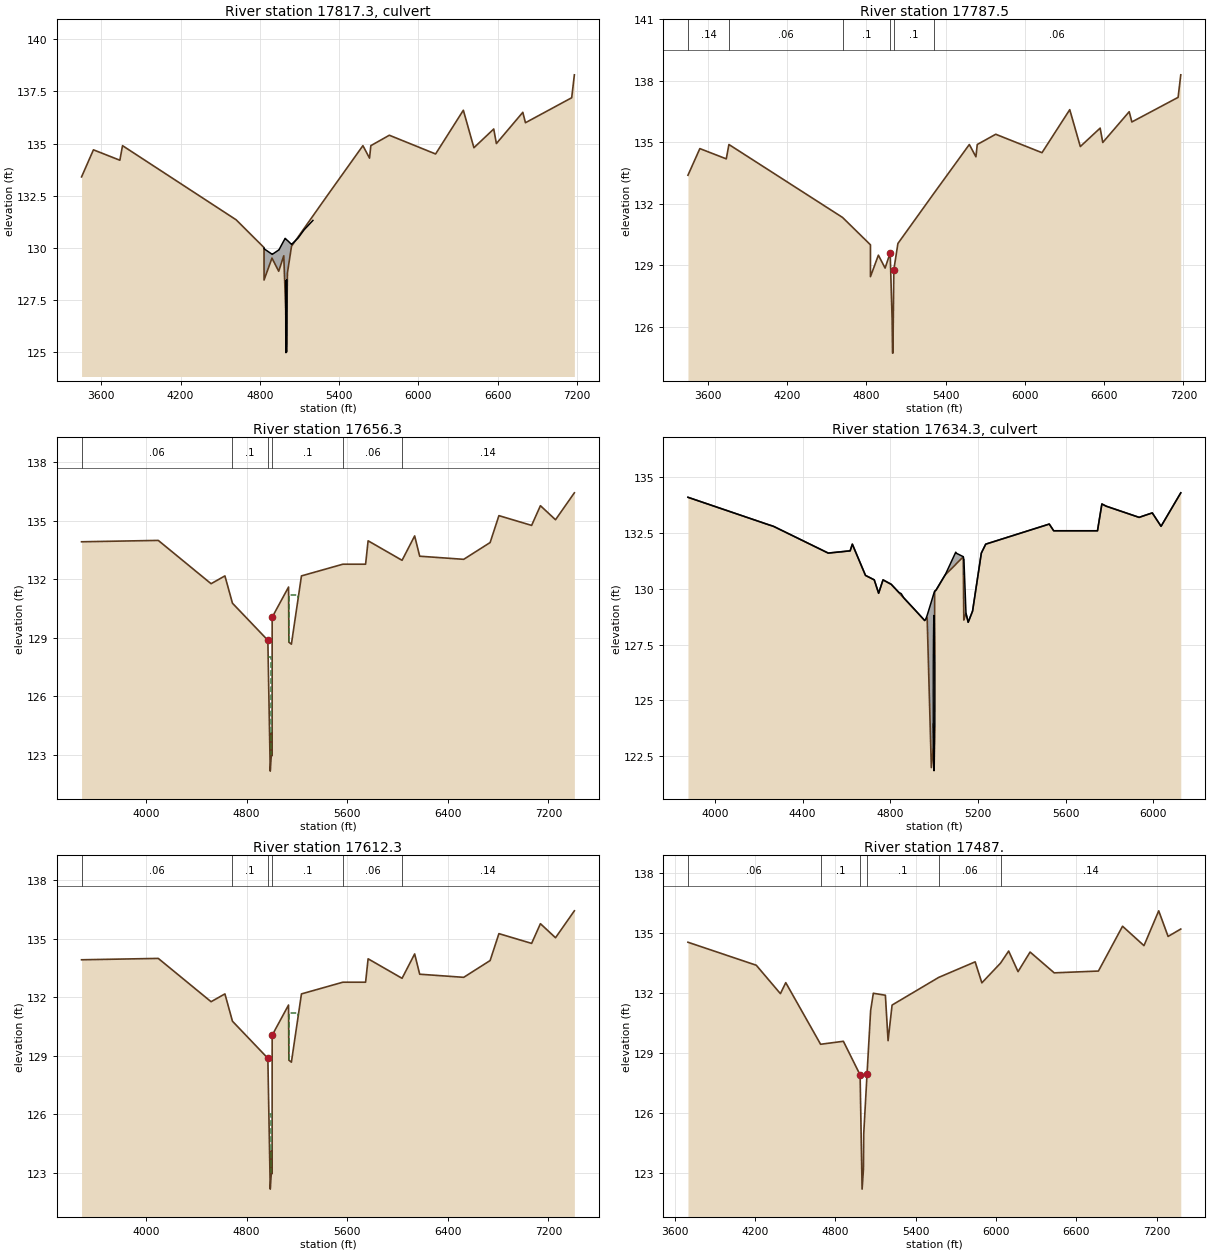
Type RM Length L Ch R = 2 ,17817.3 ,,,
BEGIN DESCRIPTION:
KLEIN CEMETERY RD  Field Surveyed negative culvert slope
Structure ID: K131-00-00-S8
END DESCRIPTION:
Bridge Culvert--1,0,-1,-1, 0
Deck Dist Width WeirC Skew NumUp NumDn MinLoCord MaxHiCord MaxSubmerge Is_Ogee
10,30,2.6,0, 24, 24, , , 0.95, 0, ,,,
  4831.9 4832.01    4892  4893.5  4942.9  4944.1  4981.2  4983.4  4990.6  4991.6
  4996.1  4997.4  4997.9  4999.2  5002.1  5002.6  5008.9  5039.8    5040  5088.9
  5089.1  5136.2  5136.6  5201.7
  129.97  129.95  129.69  129.68  129.89  129.89  130.33  130.35  130.44  130.45
  130.42  130.42  130.41   130.4  130.39  130.38  130.35  130.16  130.16  130.46
  130.46  130.87  130.87  131.31
                                                                                
                                                                                
                                
  4831.9 4832.01    4892  4893.5  4942.9  4944.1  4981.2  4983.4  4990.6  4991.6
  4996.1  4997.4  4997.9  4999.2  5002.1  5002.6  5008.9  5039.8    5040  5088.9
  5089.1  5136.2  5136.6  5201.7
  129.97  129.95  129.69  129.68  129.89  129.89  130.33  130.35  130.44  130.45
  130.42  130.42  130.41   130.4  130.39  130.38  130.35  130.16  130.16  130.46
  130.46  130.87  130.87  131.31
                                                                                
                                                                                
                                
BR Coef= 1 , 1 , 0 ,1.25, 0 ,,,0.8,0,2,0,
WSPro=,,,, 1 ,,,, 0 ,,,, 0 ,,,,-1 ,-1 ,-1 , 0 , 0 , 0 , 0 , 0
Culvert=1,3.5,,30,0.015,0.2,1,1,3,124.94,4997.2,125.01,4997.2,Culvert #1  , 0 ,10
Culvert Bottom n=0.015
Culvert=1,3.5,,30,0.015,0.2,1,1,3,124.98,5002.9,125.04,5002.9,Culvert #2  , 0 ,10
Culvert Bottom n=0.015
BR D #Sta/Elev= 79
  3450.9   133.4  3540.9   134.7  3680.9   134.6  3700.9   134.2  3720.9   134.6
  3740.9   134.2  3760.9   134.9  4580.9   131.5  4600.9  131.94  4620.9  131.34
  4785.9  130.28    4786  130.28  4788.4  130.54  4831.2  130.01  4831.9     130
 4832.01  128.45    4892   129.5  4893.5  129.48  4942.9  128.87  4944.1  128.89
  4981.2  129.61  4983.4  128.77  4990.6  127.05  4991.6  126.92  4996.1  126.33
  4997.4  125.29  4997.9  124.97  4999.2  124.72  5002.1  124.72  5002.6  125.31
  5008.9  128.79  5039.8  130.07    5040  130.07  5088.9  130.19  5089.1  130.19
  5136.2  130.68  5136.6  130.68  5201.7  131.34  5202.3  131.58  5207.5  131.29
  5210.2   131.1  5310.2   132.5  5320.2   132.1  5330.2   132.9  5380.2   133.2
  5390.2   133.6  5430.2   133.4  5440.2   133.9  5470.2   134.1  5480.2   134.5
  5530.2     134  5580.2   134.9  5610.2   134.3  5620.2   134.5  5630.2   134.3
  5640.2   134.9  5780.2   135.4  5920.2   134.8  5950.2   135.1  5970.2   134.7
  6010.2   135.2  6040.2   134.8  6090.2   135.1  6130.2   134.5  6150.2   135.1
  6310.2   136.1  6340.2   136.6  6420.2   134.8  6570.2   135.7  6590.2     135
  6790.2   136.5  6810.2     136  6860.2   136.4  7060.2   136.7  7080.2   137.1
  7090.2   136.9  7130.2   137.5  7160.2   137.2  7180.4   138.3
BR D #Mann= 6
  3450.9     .14  3760.9     .06  4620.9      .1  4981.2    .055  5008.9      .1
  5310.2     .06
BC Design=,, 0 ,, 0 ,,,,,,
BC HTab HWMax=138.3

Type RM Length L Ch R = 1 ,17787.5 ,21.6,131.2,296.5
BEGIN DESCRIPTION:
Downstream Section of Bridge/Culvert/Weir
END DESCRIPTION:
XS GIS Cut Line= 4
       3068799.9     13945642.66      3068357.46     13944272.42
      3068096.26     13944065.12      3066338.53     13943170.61
#Sta/Elev= 30
  3450.9   133.4  3540.9   134.7  3740.9   134.2  3760.9   134.9  4620.9  131.34
  4831.2  130.01  4831.9     130 4832.01  128.45    4892   129.5  4942.9  128.87
  4981.2  129.61  4996.1  126.33  4999.2  124.72  5002.1  124.72  5008.9  128.79
  5039.8  130.07  5310.2   132.5  5580.2   134.9  5630.2   134.3  5640.2   134.9
  5780.2   135.4  6130.2   134.5  6340.2   136.6  6420.2   134.8  6570.2   135.7
  6590.2     135  6790.2   136.5  6810.2     136  7160.2   137.2  7180.4   138.3
#Mann= 6 ,-1 , 0
  3450.9     .14       0  3760.9     .06       0  4620.9      .1       0
  4981.2    .055       0  5008.9      .1       0  5310.2     .06       0
#XS Ineff= 2 , 0
       0 4985.45  126.75 5014.65       0  126.75
Permanent Ineff=
       F       F
Bank Sta=4981.2,5008.9
Exp/Cntr=0.5,0.3

Type RM Length L Ch R = 1 ,17656.3 ,43,44,54.6
BEGIN DESCRIPTION:
Upstream Section of Bridge/Culvert/Weir
END DESCRIPTION:
XS GIS Cut Line= 4
      3068803.12     13945634.19      3068392.46     13944310.68
      3068436.96     13944071.98      3066649.55     13942640.56
#Sta/Elev= 30
  3487.3  133.93  4097.3     134  4517.2  131.78  4627.2  132.18  4687.2  130.78
  4968.6  128.88  4987.7  122.17  4997.5  123.13  4997.6  124.14  4999.8  122.95
  5001.4  123.29  5002.4  124.12  5002.9  130.06  5133.3  131.61  5135.8  128.78
  5155.8  128.68  5235.8  132.18    5565  132.78  5745.8  132.78  5765.8  133.98
  6035.8  132.98  6135.9  134.23  6175.9  133.19  6525.9  133.03  6735.9  133.89
  6805.9  135.27  7065.9  134.77  7135.9  135.78  7255.9  135.06  7405.8  136.44
#Mann= 6 ,-1 , 0
  3487.3     .06       0  4687.2      .1       0  4968.6    .055       0
  5002.9      .1       0    5565     .06       0  6035.8     .14       0
#XS Ineff= 3 ,-1
    4970  4996.3     128  5003.3    5005     128  5136.7 5209.48   131.2
Permanent Ineff=
       F       F       F
Bank Sta=4968.6,5002.9
Exp/Cntr=0.5,0.3

Type RM Length L Ch R = 2 ,17634.3 ,,,
BEGIN DESCRIPTION:
150'+/- DS KLEIN CEMETERY ROAD Field Surveyed negative culvert slope
Structure ID: K131-00-00-S7
END DESCRIPTION:
Bridge Culvert--1,0,-1,-1, 0
Deck Dist Width WeirC Skew NumUp NumDn MinLoCord MaxHiCord MaxSubmerge Is_Ogee
10,22,2.6,0, 50, 50, , , 0.95, 0, ,,,
  3877.2  4242.2  4267.2  4517.2  4617.2  4627.2  4687.2  4727.2  4747.2  4767.2
  4804.7  4839.4  4850.4  4861.7  4912.7  4957.2  4962.2  4968.6  4987.7  4997.5
  4997.6  4999.8  5001.1  5001.4  5002.4  5002.9  5009.2  5051.5  5051.7    5099
  5100.3  5133.3  5135.8  5136.4  5145.8  5155.8  5175.8  5215.8  5235.8  5525.8
  5545.8    5565  5745.8  5765.8  5785.8  5935.8  5956.3  5995.8  6035.8  6125.8
   134.1  132.88   132.8   131.6   131.7     132   130.6   130.4   129.8   130.4
   130.2  129.84  129.78   129.6  129.06  128.58  128.64  128.81  129.42  129.74
  129.74  129.81  129.85  129.85  129.87  129.89  129.95  130.64  130.64  131.64
   131.6  131.44   131.3   131.3   128.9   128.5     129   131.6     132   132.9
   132.6   132.6   132.6   133.8   133.7   133.2  133.27   133.4   132.8   134.3
   134.1  132.88   132.8   131.6   131.7     132   130.6   130.4   129.8   130.4
   130.2  129.83  129.71  129.59  129.05  128.58  128.63   128.7  121.99  122.95
  123.96  122.77  123.05  123.11  123.94  129.88  129.93  130.63  130.63  131.09
  131.11  131.43   128.6  128.62   128.9   128.5     129   131.6     132   132.9
   132.6   132.6   132.6   133.8   133.7   133.2  133.27   133.4   132.8   134.3
  3877.2  4242.2  4267.2  4517.2  4617.2  4627.2  4687.2  4727.2  4747.2  4767.2
  4804.7  4839.4  4850.4  4861.7  4912.7  4957.2  4962.2  4968.6  4987.7  4997.5
  4997.6  4999.8  5001.1  5001.4  5002.4  5002.9  5009.2  5051.5  5051.7    5099
  5100.3  5133.3  5135.8  5136.4  5145.8  5155.8  5175.8  5215.8  5235.8  5525.8
  5545.8    5565  5745.8  5765.8  5785.8  5935.8  5956.3  5995.8  6035.8  6125.8
   134.1  132.88   132.8   131.6   131.7     132   130.6   130.4   129.8   130.4
   130.2  129.84  129.78   129.6  129.06  128.58  128.64  128.81  129.42  129.74
  129.74  129.81  129.85  129.85  129.87  129.89  129.95  130.64  130.64  131.64
   131.6  131.44   131.3   131.3   128.9   128.5     129   131.6     132   132.9
   132.6   132.6   132.6   133.8   133.7   133.2  133.27   133.4   132.8   134.3
   134.1  132.88   132.8   131.6   131.7     132   130.6   130.4   129.8   130.4
   130.2  129.83  129.71  129.59  129.05  128.58  128.63   128.7  121.99  122.95
  123.96  122.77  123.05  123.11  123.94  129.88  129.93  130.63  130.63  131.09
  131.11  131.43   128.6  128.62   128.9   128.5     129   131.6     132   132.9
   132.6   132.6   132.6   133.8   133.7   133.2  133.27   133.4   132.8   134.3
BR Coef= 1 , 1 , 0 ,1.25, 0 ,,,0.8,0,2,0,
WSPro=,,,, 1 ,,,, 0 ,,,, 0 ,,,,-1 ,-1 ,-1 , 0 , 0 , 0 , 0 , 0
Culvert=1,7,,22,0.015,0.2,1,1,3,121.83,4999.8,122.27,4999.8,Culvert #1  , 0 ,10
Culvert Bottom n=0.015
BR U #Sta/Elev= 50
  3877.2   134.1  4242.2  132.88  4267.2   132.8  4517.2   131.6  4617.2   131.7
  4627.2     132  4687.2   130.6  4727.2   130.4  4747.2   129.8  4767.2   130.4
  4804.7   130.2  4839.4  129.83  4850.4  129.71  4861.7  129.59  4912.7  129.05
  4957.2  128.58  4962.2  128.63  4968.6   128.7  4987.7  121.99  4997.5  122.95
  4997.6  123.96  4999.8  122.77  5001.1  123.05  5001.4  123.11  5002.4  123.94
  5002.9  129.88  5009.2  129.93  5051.5  130.63  5051.7  130.63    5099  131.09
  5100.3  131.11  5133.3  131.43  5135.8   128.6  5136.4  128.62  5145.8   128.9
  5155.8   128.5  5175.8     129  5215.8   131.6  5235.8     132  5525.8   132.9
  5545.8   132.6    5565   132.6  5745.8   132.6  5765.8   133.8  5785.8   133.7
  5935.8   133.2  5956.3  133.27  5995.8   133.4  6035.8   132.8  6125.8   134.3
BR U #Mann= 6
  3877.2     .06  4687.2      .1  4968.6    .055  5002.9      .1    5565     .06
  6035.8     .14
BR U Banks=4968.6,5002.9
BR D #Sta/Elev= 50
  3877.2   134.1  4242.2  132.88  4267.2   132.8  4517.2   131.6  4617.2   131.7
  4627.2     132  4687.2   130.6  4727.2   130.4  4747.2   129.8  4767.2   130.4
  4804.7   130.2  4839.4  129.83  4850.4  129.71  4861.7  129.59  4912.7  129.05
  4957.2  128.58  4962.2  128.63  4968.6   128.7  4987.7  121.99  4997.5  122.95
  4997.6  123.96  4999.8  122.77  5001.1  123.05  5001.4  123.11  5002.4  123.94
  5002.9  129.88  5009.2  129.93  5051.5  130.63  5051.7  130.63    5099  131.09
  5100.3  131.11  5133.3  131.43  5135.8   128.6  5136.4  128.62  5145.8   128.9
  5155.8   128.5  5175.8     129  5215.8   131.6  5235.8     132  5525.8   132.9
  5545.8   132.6    5565   132.6  5745.8   132.6  5765.8   133.8  5785.8   133.7
  5935.8   133.2  5956.3  133.27  5995.8   133.4  6035.8   132.8  6125.8   134.3
BR D #Mann= 6
  3877.2     .06  4687.2      .1  4968.6    .055  5002.9      .1    5565     .06
  6035.8     .14
BR D Banks=4968.6,5002.9
BC Design=,, 0 ,, 0 ,,,,,,
BC HTab HWMax=136.44

Type RM Length L Ch R = 1 ,17612.3 ,140.5,125.3,18.8
BEGIN DESCRIPTION:
Downstream Section of Bridge/Culvert/Weir;
END DESCRIPTION:
XS GIS Cut Line= 4
      3068841.32     13945629.09      3068432.12     13944310.31
      3068477.91     13944064.69      3066681.15     13942625.78
#Sta/Elev= 30
  3487.3  133.93  4097.3     134  4517.2  131.78  4627.2  132.18  4687.2  130.78
  4968.6  128.88  4987.7  122.17  4997.5  123.13  4997.6  124.14  4999.8  122.95
  5001.4  123.29  5002.4  124.12  5002.9  130.06 5133.09  131.61  5135.8  128.78
  5155.8  128.68  5235.8  132.18    5565  132.78  5745.8  132.78  5765.8  133.98
  6035.8  132.98  6135.9  134.23  6175.9  133.19  6525.9  133.03  6735.9  133.89
  6805.9  135.27  7065.9  134.77  7135.9  135.78  7255.9  135.06  7405.8  136.44
#Mann= 6 ,-1 , 0
  3487.3     .06       0  4687.2      .1       0  4968.6    .055       0
  5002.9      .1       0    5565     .06       0  6035.8     .14       0
#XS Ineff= 3 ,-1
  4976.5  4996.3     126  5003.3    5005     126  5136.7 5209.48   131.2
Permanent Ineff=
       F       F       F
Bank Sta=4968.6,5002.9
Exp/Cntr=0.5,0.3

Type RM Length L Ch R = 1 ,17487.  ,229.2,234.99,244.3
BEGIN DESCRIPTION:
K131-00-00-S07_UNKNOWN RD. 2_DS - XS 1
END DESCRIPTION:
XS GIS Cut Line= 4
      3068794.44       13945448.      3068564.23     13944233.67
      3068555.97     13944117.01      3066785.59      13942610.5
#Sta/Elev= 30
  3700.3  134.53  4210.3  133.38  4390.3  131.96  4430.3  132.51  4690.3  129.43
  4860.3  129.58  4985.1   127.9    5000  122.19 5010.02  123.17 5012.17  124.96
  5036.9  127.95  5063.8  131.12  5083.8  131.98  5173.8  131.88  5193.8  129.61
  5223.8  131.39    5571  132.77  5843.8  133.55  5893.8   132.5  6033.8  133.49
  6093.8  134.09  6163.8  133.06  6253.8  134.04  6433.8     133  6763.8  133.09
  6943.8  135.33  7103.8  134.36  7213.8   136.1  7283.8  134.82  7378.4  135.19
#Mann= 6 ,-1 , 0
  3700.3     .06       0  4690.3      .1       0  4985.1    .055       0
  5036.9      .1       0    5571     .06       0  6033.8     .14       0
Bank Sta=4985.1,5036.9
Exp/Cntr=0.3,0.1