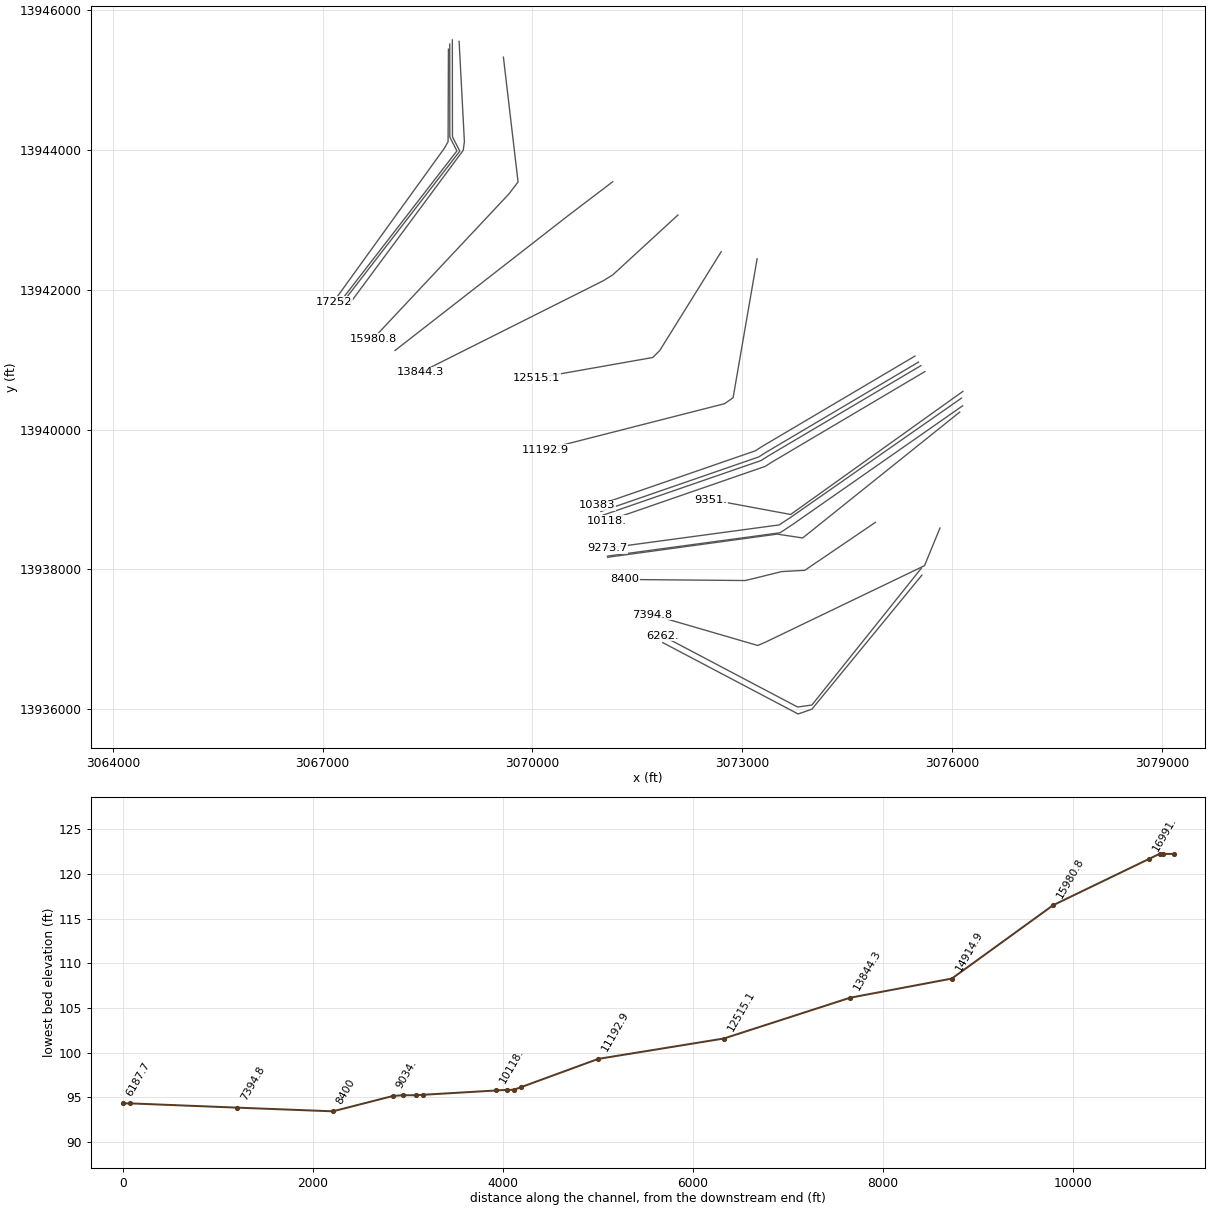
HEC-RAS study K131-00-00.prj: K131-00-00

--- K131-00-00.g04 (geometry) --- (continued)

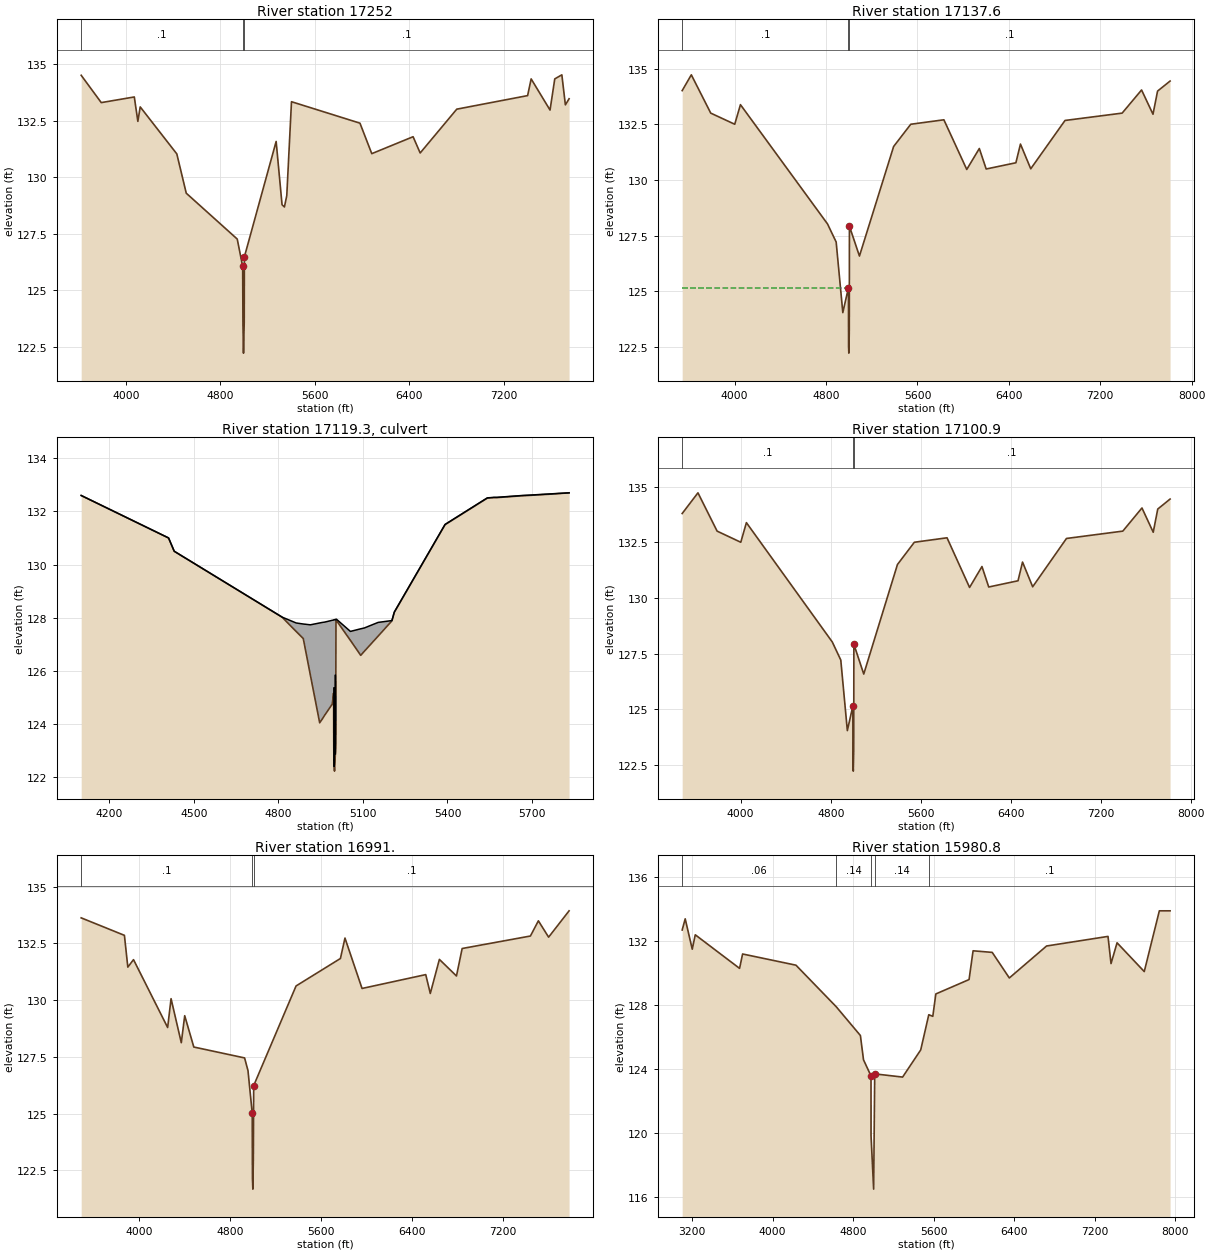
Type RM Length L Ch R = 1 ,17252   ,24.4,114.4,177.3
BEGIN DESCRIPTION:
K131-00-00-S10_UNKNOWN RD. 1_US - XS 4
END DESCRIPTION:
XS GIS Cut Line= 4
        3068798.       13945434.      3068793.21     13944112.52
      3068739.03     13944017.24       3067157.5     13941827.33
#Sta/Elev= 30
  3621.7  134.52  3791.7  133.31  4071.7  133.56  4101.7  132.48  4121.7  133.12
  4431.7  131.04  4511.7   129.3  4943.5  127.27 4989.55  126.06 4991.97  123.51
 4996.58  122.22  5002.7  123.58 5004.01  126.48  5273.1  131.59  5323.1  128.79
  5343.1  128.69  5363.1  129.19  5403.1  133.35  5983.1   132.4  6083.1  131.05
  6433.1   131.8  6493.1  131.08  6803.1  133.02  7403.1  133.62  7433.1  134.36
  7593.1  132.98  7633.1  134.36  7693.1  134.54  7723.1  133.21  7754.4  133.48
#Mann= 3 ,-1 , 0
  3621.7      .1       0 4989.55    .055       0 5004.01      .1       0
Bank Sta=4989.55,5004.01
Exp/Cntr=0.5,0.3

Type RM Length L Ch R = 1 ,17137.6 ,35,36.7,40.4
BEGIN DESCRIPTION:
Upstream Section of Bridge/Culvert/Weir
END DESCRIPTION:
XS GIS Cut Line= 4
  3068816.27872413945506.7700394       3068817.8     13944178.61
      3068918.94     13943980.36       3067254.3     13941829.88
#Sta/Elev= 30
  3540.9  134.02  3620.9  134.73  3790.9  133.01  4000.9  132.51  4050.9  133.39
  4813.3  128.03  4888.6  127.22  4946.8  124.05  4996.2  125.17  4997.3  122.54
  4999.4  122.23  5003.2  123.13  5003.7  123.91  5004.7  127.93  5092.4  126.59
  5391.5  131.51  5541.5  132.51  5831.5  132.71  6031.6  130.48  6141.6  131.42
  6201.6   130.5  6461.6  130.78  6501.6  131.62  6591.6  130.51  6891.6  132.68
  7391.6  133.01  7561.6  134.05  7661.6  132.96  7701.6     134  7811.1  134.45
#Mann= 3 ,-1 , 0
  3540.9      .1       0  4996.2    .055       0  5004.7      .1       0
#XS Ineff= 2 , 0
       0  4986.9  125.17    5014       0     126
Permanent Ineff=
       F       F
Bank Sta=4996.2,5004.7
Exp/Cntr=0.5,0.3

Type RM Length L Ch R = 2 ,17119.3 ,,,
BEGIN DESCRIPTION:
UNNAMED RD 650' D/S OF KLEIN CEMETERY RD  Field Surveyed one of the two culverts with negative culvert slope
Structure ID: K131-00-00-S10
Dirt road with wooden boards as headwalls VRR
END DESCRIPTION:
Bridge Culvert--1,0,-1,-1, 0
Deck Dist Width WeirC Skew NumUp NumDn MinLoCord MaxHiCord MaxSubmerge Is_Ogee
10,18,2.6,0, 36, 36, , , 0.95, 0, ,,,
  4100.8  4410.8  4430.8  4813.3  4863.2  4888.6  4913.7  4946.8  4956.6  4963.7
  4991.3  4996.2  4996.8  4997.3  4999.4  5001.2  5003.2  5003.7  5004.7  5006.4
    5056  5062.6  5092.4    5105  5153.9  5203.1  5211.5  5391.5  5535.4  5541.5
  5565.4  5575.4  5665.4  5685.4  5765.4  5831.5
   132.6     131   130.5  128.02   127.8  127.76  127.73   127.8  127.82  127.83
   127.9  127.91  127.92  127.92  127.92  127.93  127.93  127.93  127.94  127.94
  127.48   127.5  127.58  127.61  127.82  127.89  128.21  131.51  132.47  132.51
  132.53  132.53   132.6  132.61  132.66   132.7
   132.6     131   130.5  128.02  127.48  127.21  125.84  124.04  124.19  124.31
  124.74  125.16   123.2  122.53  122.22  122.57  123.12   123.9  127.92  127.89
  127.14  127.04  126.58  126.73   127.3  127.88   128.2   131.5  132.46   132.5
  132.52  132.52  132.59   132.6  132.65   132.7
  4100.8  4410.8  4430.8  4813.3  4863.2  4888.6  4913.7  4946.8  4956.6  4963.7
  4991.3  4996.2  4996.8  4997.3  4999.4  5001.2  5003.2  5003.7  5004.7  5006.4
    5056  5062.6  5092.4    5105  5153.9  5203.1  5211.5  5391.5  5535.4  5541.5
  5565.4  5575.4  5665.4  5685.4  5765.4  5831.5
  132.81  131.21  130.71  128.23   127.8  127.76  127.73   127.8  127.82  127.83
   127.9  127.91  127.92  127.92  127.92  127.93  127.93  127.93  128.13   128.1
  127.48   127.5  127.58  127.61  127.82  128.09  128.41  131.71  132.67  132.71
  132.73  132.73   132.8  132.81  132.86  132.91
  132.81  131.21  130.71  128.23  127.69  127.42  126.05  124.25   124.4  124.52
  124.95  125.37  123.41  122.74  122.43  122.78  123.33  124.11  128.13   128.1
  127.35  127.25  126.79  126.94  127.51  128.09  128.41  131.71  132.67  132.71
  132.73  132.73   132.8  132.81  132.86  132.91
BR Coef= 1 , 1 , 0 ,1.25, 0 ,,,0.8,0,2,0,
WSPro=,,,, 1 ,,,, 0 ,,,, 0 ,,,,-1 ,-1 ,-1 , 0 , 0 , 0 , 0 , 0
Culvert=1,3,,18,0.024,0.9,1,2,3,122.38,4998.4,122.58,4998.4,Culvert #1  , 0 ,10
Culvert Bottom n=0.024
Culvert=1,3,,18,0.024,0.9,1,2,3,122.85,5002.5,122.47,5002.5,Culvert #2  , 0 ,10
Culvert Bottom n=0.024
BR U #Sta/Elev= 36
  4100.8   132.6  4410.8     131  4430.8   130.5  4813.3  128.02  4863.2  127.48
  4888.6  127.21  4913.7  125.84  4946.8  124.04  4956.6  124.19  4963.7  124.31
  4991.3  124.74  4996.2  125.16  4996.8   123.2  4997.3  122.53  4999.4  122.22
  5001.2  122.57  5003.2  123.12  5003.7   123.9  5004.7  127.92  5006.4  127.89
    5056  127.14  5062.6  127.04  5092.4  126.58    5105  126.73  5153.9   127.3
  5203.1  127.88  5211.5   128.2  5391.5   131.5  5535.4  132.46  5541.5   132.5
  5565.4  132.52  5575.4  132.52  5665.4  132.59  5685.4   132.6  5765.4  132.65
  5831.5   132.7
BR U #Mann= 3
  4100.8      .1  4996.2    .055  5004.7      .1
BR U Banks=4996.2,5004.7
BR D #Sta/Elev= 36
  4100.8  132.81  4410.8  131.21  4430.8  130.71  4813.3  128.23  4863.2  127.69
  4888.6  127.42  4913.7  126.05  4946.8  124.25  4956.6   124.4  4963.7  124.52
  4991.3  124.95  4996.2  125.37  4996.8  123.41  4997.3  122.74  4999.4  122.43
  5001.2  122.78  5003.2  123.33  5003.7  124.11  5004.7  128.13  5006.4   128.1
    5056  127.35  5062.6  127.25  5092.4  126.79    5105  126.94  5153.9  127.51
  5203.1  128.09  5211.5  128.41  5391.5  131.71  5535.4  132.67  5541.5  132.71
  5565.4  132.73  5575.4  132.73  5665.4   132.8  5685.4  132.81  5765.4  132.86
  5831.5  132.91
BR D #Mann= 3
  4100.8      .1  4996.2    .055  5004.7      .1
BR D Banks=4996.2,5004.7
BC Design=,, 0 ,, 0 ,,,,,,
BC HTab HWMax=134.73

Type RM Length L Ch R = 1 ,17100.9 ,167.8,109.9,39.1
BEGIN DESCRIPTION:
Downstream Section of Bridge/Culvert/Weir
END DESCRIPTION:
XS GIS Cut Line= 4
        3068854.      13945566.2      3068855.58     13944182.83
      3068960.31     13943977.56      3067287.91     13941817.04
#Sta/Elev= 30
  3480.9   133.8  3620.9  134.73  3790.9  133.01  4000.9  132.51  4050.9  133.39
  4813.3  128.03  4888.6  127.22  4946.8  124.05  4996.2  125.17  4997.3  122.54
  4999.4  122.23  5003.2  123.13  5003.7  123.91  5004.7  127.93  5092.4  126.59
  5391.5  131.51  5541.5  132.51  5831.5  132.71  6031.6  130.48  6141.6  131.42
  6201.6   130.5  6461.6  130.78  6501.6  131.62  6591.6  130.51  6891.6  132.68
  7391.6  133.01  7561.6  134.05  7661.6  132.96  7701.6     134  7811.1  134.45
#Mann= 3 ,-1 , 0
  3480.9      .1       0  4996.2    .055       0  5004.7      .1       0
#XS Ineff= 2 , 0
       0  4986.9   124.8    5014       0   124.8
Permanent Ineff=
       F       F
Bank Sta=4996.2,5004.7
Exp/Cntr=0.5,0.3

Type RM Length L Ch R = 1 ,16991.  ,1025.2,1010.2,962.5
BEGIN DESCRIPTION:
K131-00-00-S10_UNKNOWN RD. 1_DS - XS 1
END DESCRIPTION:
XS GIS Cut Line= 4
       3068950.8       13945545.      3069026.28      13944111.5
      3069009.74     13943990.25      3067384.71     13941796.67
#Sta/Elev= 30
  3490.8  133.62  3870.8  132.85  3900.8  131.45  3950.8  131.78  4250.8  128.79
  4280.8  130.06  4370.8  128.12  4400.8  129.31  4480.8  127.93  4927.1  127.45
  4957.1  126.89 4994.37  125.01 4994.39  124.61 4996.24  122.14 4999.81  121.67
 5003.99  122.96  5007.1  126.23  5379.5  130.62  5769.5  131.83  5809.5  132.73
  5959.5  130.51  6519.5  131.12  6559.5  130.29  6639.5  131.79  6789.5  131.06
  6839.5  132.27  7439.5  132.82  7509.5  133.49  7599.5  132.77  7779.4  133.93
#Mann= 3 ,-1 , 0
  3490.8      .1       0 4994.39    .055       0  5007.1      .1       0
Bank Sta=4994.37,5007.1
Exp/Cntr=0.3,0.1

Type RM Length L Ch R = 1 ,15980.8 ,1100,1065.9,889
BEGIN DESCRIPTION:
Cross Section K131-00-00-X05 **Note**
Cross-section has 0.3 and 0.5 expansion/contraction coefficients due to the change in the channel geometry.
END DESCRIPTION:
XS GIS Cut Line= 4
      3069584.16      13945320.4      3069793.63     13943537.11
      3069664.16     13943367.19      3067723.01     13941298.86
#Sta/Elev= 30
    3102   132.7    3132   133.4    3202   131.5    3232   132.4    3672   130.3
    3702   131.2    4232   130.5    4632   127.9    4872   126.1  4902.9  124.58
  4977.5  123.57  4977.6  119.84  5003.6  116.49  5014.2   123.7  5291.2   123.5
  5471.2   125.2  5551.2   127.4  5591.2   127.3  5621.2   128.7  5951.2   129.6
  5991.2   131.4  6181.2   131.3  6351.2   129.7  6721.2   131.7  7331.2   132.3
  7361.2   130.6  7421.2   131.9  7691.2   130.1  7841.2   133.9  7947.7   133.9
#Mann= 5 ,-1 , 0
    3102     .06       0    4632     .14       0  4977.5    .055       0
  5014.2     .14       0  5551.2      .1       0
Bank Sta=4977.5,5014.2
Exp/Cntr=0.5,0.3

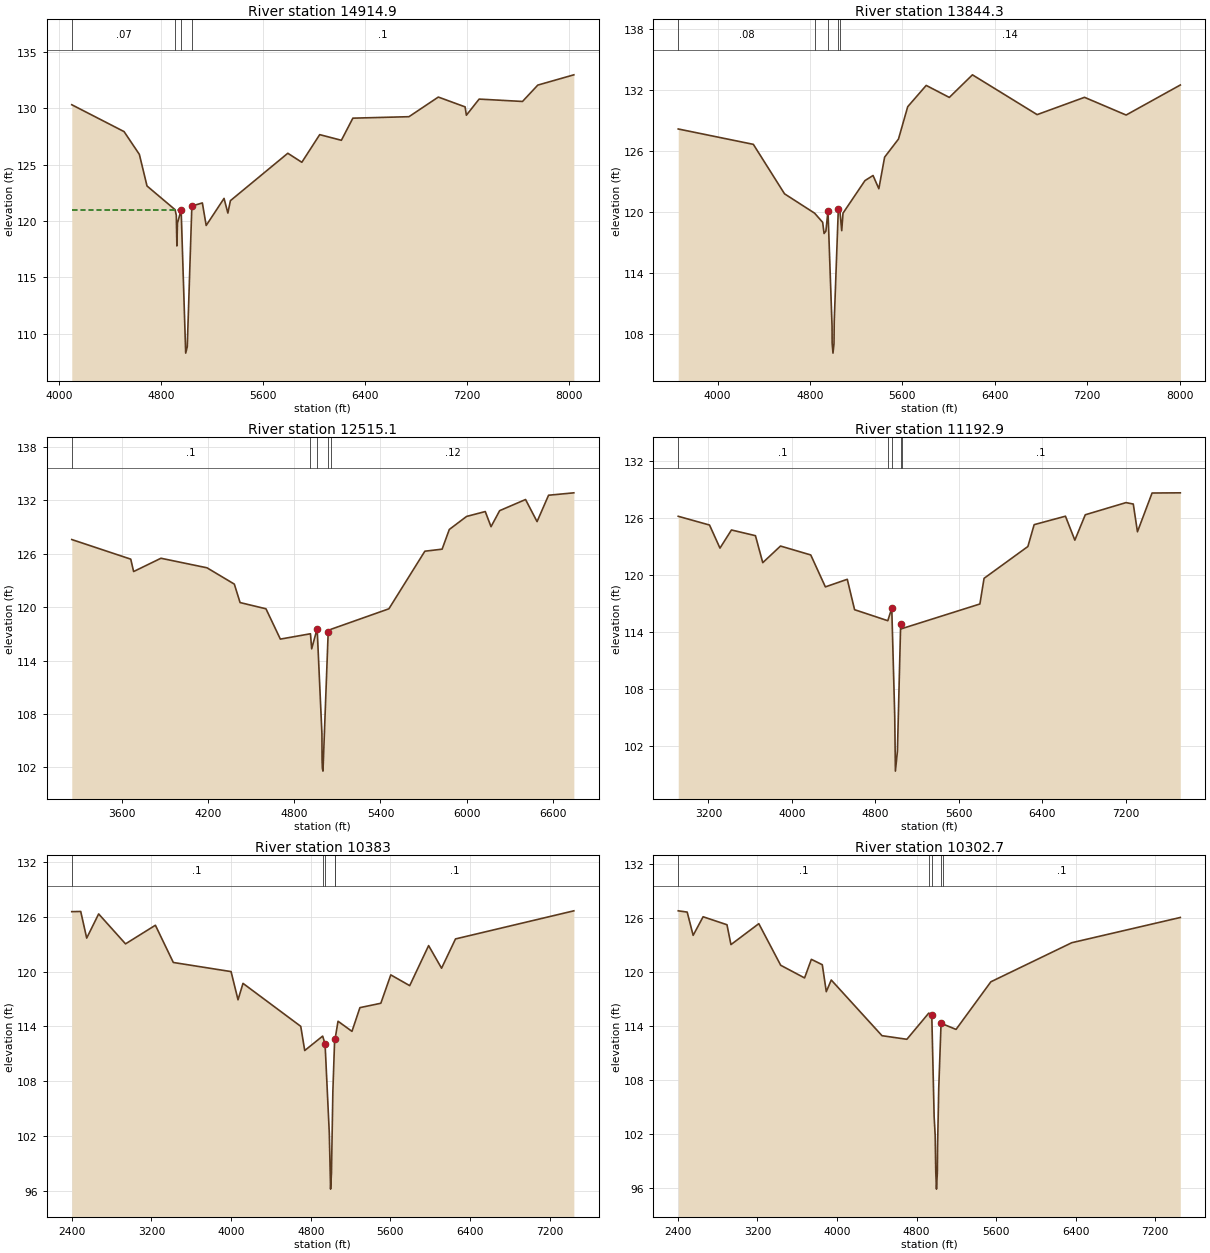
Type RM Length L Ch R = 1 ,14914.9 ,1073.3,1070.6,1065.3
BEGIN DESCRIPTION:
Cross Section K131-00-00-X04
END DESCRIPTION:
XS GIS Cut Line= 4
      3071146.06     13943539.54      3070493.54     13943043.53
      3070364.08     13942942.39       3068034.1     13941128.84
#Sta/Elev= 30
  4101.4   130.3  4511.4  127.92  4631.4   125.9  4691.4   123.1  4911.4     121
    4921   120.5  4925.6  117.79    4930  119.81    4959  120.98  4994.6  108.29
  5006.9  108.85  5042.9  121.32  5125.3   121.6  5155.3   119.6  5295.3     122
  5325.3   120.7  5345.3   121.8  5795.3     126  5905.3   125.2  6045.3  127.65
  6215.3  127.15  6305.3  129.11  6745.3  129.24  6975.3  130.98  7185.3  130.11
  7195.3  129.37  7295.3   130.8  7635.3  130.59  7755.3  132.04  8037.9  132.95
#Mann= 4 ,-1 , 0
  4101.4     .07       0  4911.4    .045       0    4959    .045       0
  5042.9      .1       0
#XS Ineff= 2 , 0
       0 4950.45  120.98 5044.07       0  121.31
Permanent Ineff=
       F       F
Bank Sta=4959,5042.9
Exp/Cntr=0.3,0.1

Type RM Length L Ch R = 1 ,13844.3 ,1301.4,1329.2,1357.5
BEGIN DESCRIPTION:
Cross Section K131-00-00-X03A
END DESCRIPTION:
XS GIS Cut Line= 4
      3072080.29     13943065.13      3071148.95     13942210.11
      3071011.39     13942125.15      3068401.78     13940817.15
#Sta/Elev= 30
  3660.2  128.17  4310.2  126.66  4580.2   121.8  4840.2   119.9  4910.2     119
  4922.3   117.9    4938  118.13  4956.2  120.13  4991.4  108.78  4992.1  107.14
  4999.4  106.15  5008.1  107.05  5010.2  109.27  5045.6  120.31  5059.7  120.07
  5075.1  118.18  5086.2   119.9  5276.2   123.1  5346.2   123.6  5396.2   122.3
  5446.2   125.4  5566.2  127.18  5646.2  130.36  5806.2  132.45  6006.2  131.27
  6206.2  133.49  6766.2  129.58  7176.2  131.28  7536.2  129.54  8005.2  132.49
#Mann= 5 ,-1 , 0
  3660.2     .08       0  4840.2    .045       0  4956.2    .045       0
  5045.6    .045       0  5059.7     .14       0
Bank Sta=4956.2,5045.6
Exp/Cntr=0.3,0.1

Type RM Length L Ch R = 1 ,12515.1 ,1333.3,1322.2,1309.9
BEGIN DESCRIPTION:
Cross Section K131-00-00-X3
END DESCRIPTION:
XS GIS Cut Line= 4
      3072698.45     13942540.47      3071820.54      13941129.9
       3071719.4     13941028.75      3070059.38     13940735.69
#Sta/Elev= 30
  3254.2  127.57  3664.2  125.37  3684.2  123.98  3874.2  125.47  4194.2   124.4
  4384.2  122.57  4424.2   120.5  4604.2   119.8  4704.2   116.4  4913.5     117
  4921.9  115.31    4960  117.57  4993.2   105.8  4994.1  102.91  4996.3   101.9
  5000.5  101.59  5036.7  117.17  5055.7   117.5  5458.7   119.8  5708.7  126.26
  5828.7  126.49  5878.7   128.7  5998.7  130.16  6128.7  130.71  6168.7  129.01
  6228.7  130.81  6408.7  132.06  6488.7  129.58  6568.7  132.54  6744.4  132.81
#Mann= 5 ,-1 , 0
  3254.2      .1       0  4913.5    .045       0    4960    .045       0
  5036.7    .045       0  5055.7     .12       0
Bank Sta=4960,5036.7
Exp/Cntr=0.3,0.1

Type RM Length L Ch R = 1 ,11192.9 ,810.6,809.9,794.6
BEGIN DESCRIPTION:
Cross Section K131-00-00-X2
Levees are not FEMA regulated levees, levee to allow proper modeling.
END DESCRIPTION:
XS GIS Cut Line= 4
      3073211.57     13942437.45      3072868.39     13940454.26
      3072747.02      13940369.3      3070178.57     13939714.12
#Sta/Elev= 30
  2910.1  126.13  3210.1  125.21  3310.1  122.78  3420.1  124.69  3650.1  124.09
  3720.1  121.25  3890.1     123  4180.1  122.06  4320.1   118.7  4530.1   119.5
  4600.1   116.3  4918.5  115.14  4956.5  116.46  4984.8  105.14  4991.2   99.31
  5010.7  101.41  5041.7  114.81  5051.2   114.3  5800.9   116.9  5840.9   119.6
  6260.9  122.95  6320.9  125.25  6620.9  126.14  6710.9  123.62  6810.9  126.29
  7200.9  127.57  7270.9  127.42  7310.9   124.5  7450.9  128.58  7721.6   128.6
#Mann= 5 ,-1 , 0
  2910.1      .1       0  4918.5    .045       0  4956.5     .04       0
  5041.7    .045       0  5051.2      .1       0
Bank Sta=4956.5,5041.7
Exp/Cntr=0.3,0.1

Type RM Length L Ch R = 1 ,10383   ,100.5,80.3,79
BEGIN DESCRIPTION:
K131-00-00-S3_SPRING CREEK OAKS_US - XS 4
END DESCRIPTION:
XS GIS Cut Line= 4
       3075468.3       13941049.      3073286.75     13939760.04
       3073185.6     13939695.31      3070927.85     13938915.36
#Sta/Elev= 30
  2399.9  126.57  2489.9  126.59  2549.9  123.67  2669.9  126.32  2939.9  123.04
  3239.9  125.08  3419.9     121  3999.9     120  4069.9  116.91  4119.9  118.71
  4699.9     114  4739.9  111.35  4919.9  112.93  4944.2  112.08 4986.69  102.28
 4999.57   96.16 5008.35   97.92 5022.58  106.89 5039.43  112.27  5044.2  112.57
  5074.3  114.56  5214.3  113.45  5294.3  116.05  5504.3  116.53  5604.3  119.64
  5794.3  118.46  5984.3  122.85  6114.3  120.37  6254.3  123.58    7443  126.66
#Mann= 5 ,-1 , 0
  2399.9      .1       0  4919.9    .045       0  4944.2     .04       0
 5039.43    .045       0  5044.2      .1       0
Bank Sta=4944.2,5044.2
Exp/Cntr=0.5,0.3

Type RM Length L Ch R = 1 ,10302.7 ,71,70.3,60.3
BEGIN DESCRIPTION:
Upstream Section of Bridge/Culvert/Weir
END DESCRIPTION:
XS GIS Cut Line= 4
      3075519.32     13940963.08      3073337.69     13939673.43
      3073236.55      13939608.7       3070978.8     13938828.75
#Sta/Elev= 30
  2404.4  126.83  2494.4  126.69  2554.4   124.1  2654.4  126.17  2894.4  125.28
  2934.4  123.07  3214.4   125.4  3434.4  120.77  3674.4  119.36  3742.7  121.43
  3852.7  120.83  3892.7  117.83  3942.7  119.13  4452.7  112.93  4702.7  112.53
  4922.4  115.44  4953.1  115.27  4976.9  103.91  4987.2  101.87  4993.3   97.76
  5000.4   95.85  5009.1   97.68  5011.2  100.49  5023.2  107.08  5046.3  114.29
  5066.4  114.22  5197.1  113.63  5547.1  118.93  6360.5  123.28  7451.5  126.09
#Mann= 5 ,-1 , 0
  2404.4      .1       0  4922.4     .04       0  4953.1     .04       0
  5046.3     .04       0  5066.4      .1       0
#XS Ineff= 2 , 0
       0    4946     114    5056       0     114
Permanent Ineff=
       F       F
Bank Sta=4953.1,5046.3
Exp/Cntr=0.5,0.3

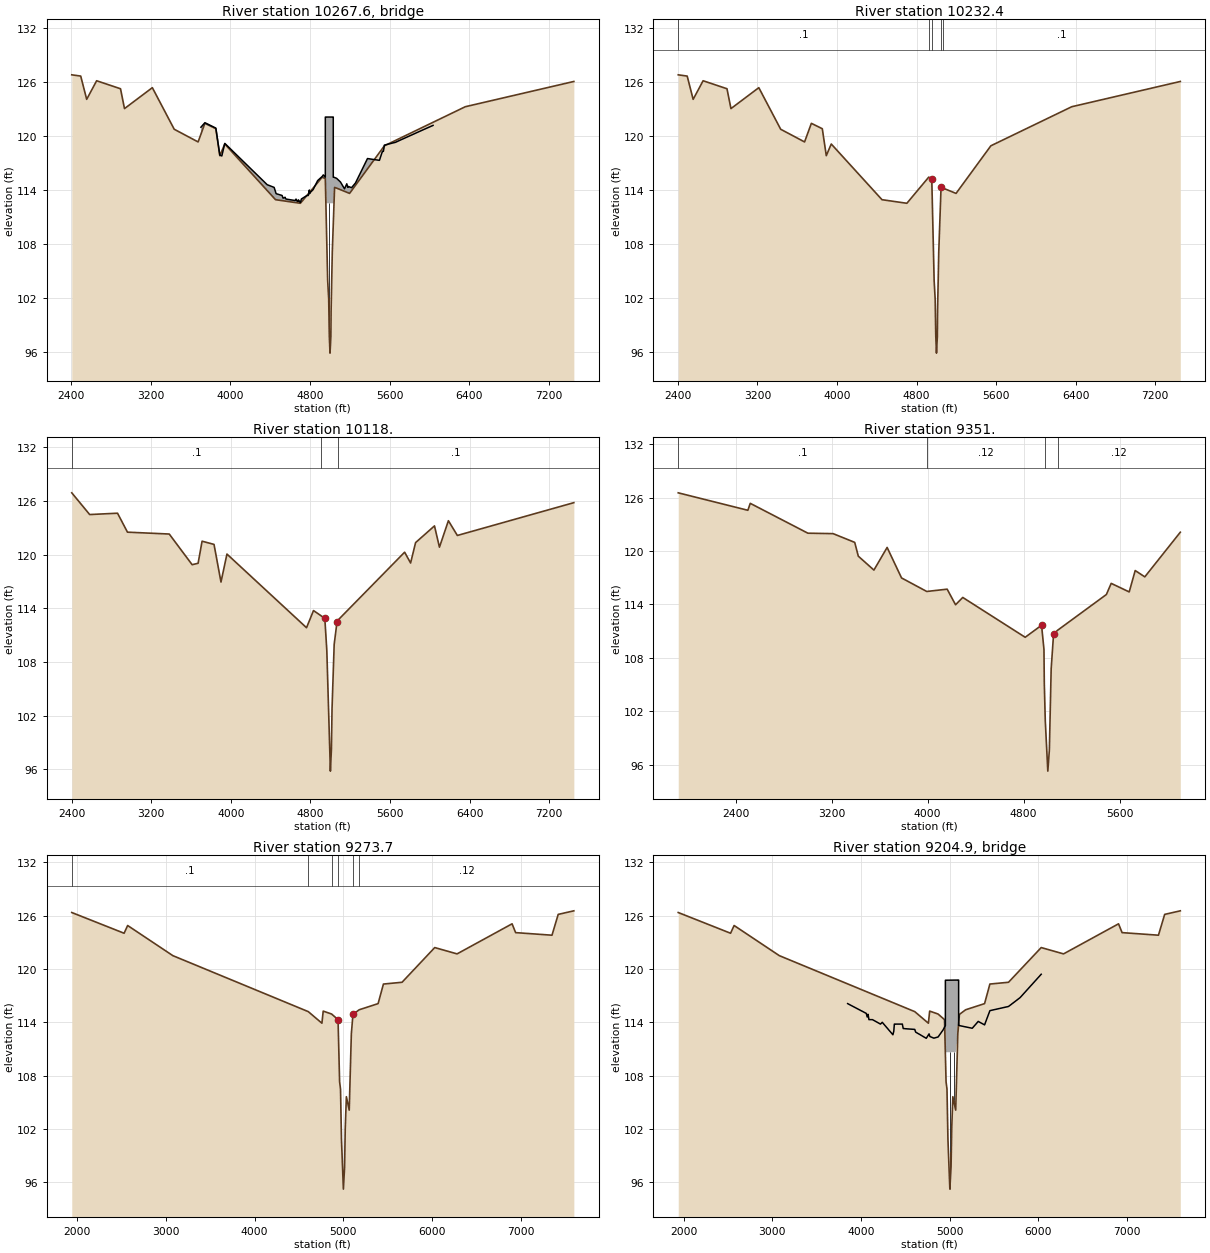
Type RM Length L Ch R = 3 ,10267.6 ,,,
BEGIN DESCRIPTION:
SPRING CREEK OAKS
NEEDS RAIL HEIGHT- Rail height entered in appears too tall closer to 5.5' high VRR
Small PIPE D/S? Too small to be a pipe VRR
Structure ID: K131-00-00-S3
END DESCRIPTION:
Bridge Culvert--1,0,-1,-1, 0
Deck Dist Width WeirC Skew NumUp NumDn MinLoCord MaxHiCord MaxSubmerge Is_Ogee
10,46,2.6,0, 88, 88, , , 0.95, 0, ,,,
  3702.7  3742.7  3852.7  3892.7  3912.7  3942.7  4368.7  4438.7  4452.7  4458.7
  4518.7  4528.7  4542.7  4548.7  4552.7  4558.7  4648.7  4658.7  4662.7  4672.7
  4678.7  4682.7  4688.7  4698.7  4702.7  4712.7  4768.7  4778.7  4782.7  4792.7
  4795.9    4799  4830.4  4876.4  4922.4  4932.8  4953.1 4953.19  4953.3 4953.41
  4958.9 4958.99  4976.9  4987.2  4993.3  5000.4  5009.1  5011.2  5023.2 5032.99
  5033.1 5033.21  5039.9 5040.33 5040.44  5046.3  5066.4  5105.4    5146    5169
    5179  5184.6  5186.2  5197.1  5217.1  5256.2  5377.1  5396.2  5406.2  5497.1
  5526.2  5527.1  5536.2  5537.1  5547.1  5556.2  5616.2  5626.2  5646.2  5657.1
  5706.2  5846.2  5866.2  5906.2  5916.2  5936.2  5946.2  6036.2
     121   121.5   120.9   117.9   117.8   119.2   114.6   114.3  113.81   113.6
   113.4   113.1  113.17   113.2  113.08     113  112.84     113  112.92  112.72
  112.75  112.91  112.82  112.67  112.61  113.01   113.4  113.39  113.41  114.01
  113.61   113.7  114.05  115.06  115.52  115.69  115.43  115.43  122.13  122.13
  122.13  122.13  122.13  122.13  122.13  122.13  122.13  122.13  122.13  122.13
  122.13  115.43  115.43  115.43  115.43   115.4  115.31   114.9  114.14   114.7
   114.3  114.38   114.4  114.35  114.27  114.79  117.51  117.48  117.46  117.31
  118.28  118.31  118.31  118.31  119.01  119.03   119.2  119.23  119.28  119.31
  119.56  120.26  120.36  120.56  120.61  120.71  120.76   121.2
                                                                                
                                                                                
                                                                                
                                                  112.53  112.53  112.53  112.53
  112.53  112.53  112.53  112.53  112.53  112.53  112.53  112.53  112.53  112.53
  112.53  112.53  112.53  112.53  112.53  112.53
                                                                                
                                                                                
                                                                
  3702.7  3742.7  3852.7  3892.7  3912.7  3942.7  4368.7  4438.7  4452.7  4458.7
  4518.7  4528.7  4542.7  4548.7  4552.7  4558.7  4648.7  4658.7  4662.7  4672.7
  4678.7  4682.7  4688.7  4698.7  4702.7  4712.7  4768.7  4778.7  4782.7  4792.7
  4795.9    4799  4830.4  4876.4  4922.4  4932.8  4953.1 4953.19  4953.3 4953.41
  4958.9 4958.99  4976.9  4987.2  4993.3  5000.4  5009.1  5011.2  5023.2 5032.99
  5033.1 5033.21  5039.9 5040.33 5040.44  5046.3  5066.4  5105.4    5146    5169
    5179  5184.6  5186.2  5197.1  5217.1  5256.2  5377.1  5396.2  5406.2  5497.1
  5526.2  5527.1  5536.2  5537.1  5547.1  5556.2  5616.2  5626.2  5646.2  5657.1
  5706.2  5846.2  5866.2  5906.2  5916.2  5936.2  5946.2  6036.2
     121   121.5   120.9   117.9   117.8   119.2   114.6   114.3  113.81   113.6
   113.4   113.1  113.17   113.2  113.08     113  112.84     113  112.92  112.72
  112.75  112.91  112.82  112.67  112.61  113.01   113.4  113.39  113.41  114.01
  113.61   113.7  114.05  115.06  115.52  115.69  115.43  115.43  122.13  122.13
  122.13  122.13  122.13  122.13  122.13  122.13  122.13  122.13  122.13  122.13
  122.13  115.43  115.43  115.43  115.43   115.4  115.31   114.9  114.14   114.7
   114.3  114.38   114.4  114.35  114.27  114.79  117.51  117.48  117.46  117.31
  118.28  118.31  118.31  118.31  119.01  119.03   119.2  119.23  119.28  119.31
  119.56  120.26  120.36  120.56  120.61  120.71  120.76   121.2
                                                                                
                                                                                
                                                                                
                                                  112.53  112.53  112.53  112.53
  112.53  112.53  112.53  112.53  112.53  112.53  112.53  112.53  112.53  112.53
  112.53  112.53  112.53  112.53  112.53  112.53
                                                                                
                                                                                
                                                                
Pier Skew, UpSta & Num, DnSta & Num=  ,4993.3, 2 ,4993.3, 2 , 0 , 0 , 0 ,,
     1.3     1.3
   96.66  113.53
     1.3     1.3
   96.63   113.5
BR Coef= 1 , 1 , 1 ,1.25, 0 ,,,0.8,0,2,0,
WSPro=,,,, 1 ,,,, 0 ,,,, 0 ,,,,-1 ,-1 ,-1 , 0 , 0 , 0 , 0 , 0
BC Design=,, 0 ,, 0 ,,,,,,
BC HTab HWMax=126.83

Type RM Length L Ch R = 1 ,10232.4 ,115,114.4,100
BEGIN DESCRIPTION:
Downstream Section of Bridge/Culvert/Weir
END DESCRIPTION:
XS GIS Cut Line= 4
      3075553.69     13940912.41      3073372.37     13939622.95
      3073269.52     13939557.12      3071009.53      13938776.4
#Sta/Elev= 30
  2404.4  126.83  2494.4  126.69  2554.4   124.1  2654.4  126.17  2894.4  125.28
  2934.4  123.07  3214.4   125.4  3434.4  120.77  3674.4  119.36  3742.7  121.43
  3852.7  120.83  3892.7  117.83  3942.7  119.13  4452.7  112.93  4702.7  112.53
  4922.4  115.44  4953.1  115.27  4976.9  103.91  4987.2  101.87  4993.3   97.76
  5000.4   95.85  5009.1   97.68  5011.2  100.49  5023.2  107.08  5046.3  114.29
  5066.4  114.22  5197.1  113.63  5547.1  118.93  6360.5  123.28  7451.5  126.09
#Mann= 5 ,-1 , 0
  2404.4      .1       0  4922.4     .04       0  4953.1     .04       0
  5046.3     .04       0  5066.4      .1       0
#XS Ineff= 2 , 0
       0    4948     113    5052       0     113
Permanent Ineff=
       F       F
Bank Sta=4953.1,5046.3
Exp/Cntr=0.5,0.3

Type RM Length L Ch R = 1 ,10118.  ,806.5,767,718.3
BEGIN DESCRIPTION:
K131-00-00-S3_SPRING CREEK OAKS_DS - XS 1
END DESCRIPTION:
XS GIS Cut Line= 4
       3075612.2      13940828.3      3073430.96     13939538.89
      3073328.11     13939473.06      3071068.12     13938692.34
#Sta/Elev= 30
  2400.7  126.91  2580.7  124.48  2860.7  124.63  2960.7  122.51  3380.7   122.3
  3610.7  118.87  3670.7  119.03  3710.7   121.5  3830.7  121.14  3900.7  116.93
  3960.7  120.06  4760.7  111.82  4830.7  113.74  4910.7  113.13  4944.6  112.86
  4964.6  109.28 5000.51   95.78  5010.6   98.17 5017.11   102.8  5038.6  109.96
  5066.8  112.45  5076.8  112.67  5746.8  120.27  5806.8  119.06  5856.8  121.34
  6046.8  123.21  6096.8  120.83  6186.8  123.79  6276.8  122.14  7447.8  125.81
#Mann= 3 ,-1 , 0
  2400.7      .1       0  4910.7     .04       0  5076.8      .1       0
Bank Sta=4944.6,5066.8
Exp/Cntr=0.3,0.1

Type RM Length L Ch R = 1 ,9351.   ,46.5,77.3,176.8
BEGIN DESCRIPTION:
K131-00-00-S2_LOUETTA_US - XS 4
END DESCRIPTION:
XS GIS Cut Line= 3
        3076154.      13940544.8      3073691.17     13938785.97
      3072554.89     13938997.01
#Sta/Elev= 30
  1922.7  126.53  2502.7  124.57  2522.7  125.35  3002.7     122  3212.7  121.95
  3392.7  120.97  3422.7  119.42  3552.7  117.86  3662.7   120.4  3782.7  116.98
  3992.7  115.46  4162.7  115.72  4232.7  113.97  4292.7  114.79  4812.7  110.32
  4949.1  111.67  4969.1  108.95 4971.83  105.19    4980  100.96 5001.23    95.3
  5014.1   97.68  5029.1  106.78  5049.1  110.68    5082   111.1  5489.1  115.12
  5529.1  116.37  5679.1  115.41  5729.1  117.81  5809.1   117.1  6104.8  122.11
#Mann= 4 ,-1 , 0
  1922.7      .1       0  3992.7     .12       0    4980     .04       0
    5082     .12       0
Bank Sta=4949.1,5049.1
Exp/Cntr=0.5,0.3

Type RM Length L Ch R = 1 ,9273.7  ,139,137.7,118.6
BEGIN DESCRIPTION:
Upstream Section of Bridge/Culvert/Weir
END DESCRIPTION:
XS GIS Cut Line= 4
      3076133.62     13940448.08      3073693.72     13938746.23
      3073527.84       13938637.      3071063.93     13938304.26
#Sta/Elev= 30
  1939.4  126.34  2529.4  124.01  2569.4  124.88  3079.4  121.49  4605.6   115.2
  4759.2   113.9  4773.8  115.26  4868.5  114.93  4941.1   114.3  4958.6  107.31
  4968.9   106.5  4979.7  100.82  5001.3   95.25  5014.8   97.73  5022.2  102.08
  5034.9  105.64  5067.1  104.13  5090.9  112.69  5109.1  114.89  5179.5  115.41
  5392.6   116.1  5452.6   118.3  5662.6   118.5    6031   122.4  6282.8  121.69
  6902.8  125.07  6942.8  124.08  7352.8  123.79  7422.8  126.13  7599.1  126.53
#Mann= 6 ,-1 , 0
  1939.4      .1       0  4605.6     .12       0  4868.5     .04       0
  4941.1     .04       0  5109.1     .04       0  5179.5     .12       0
#XS Ineff= 2 , 0
       0    4935     113    5104       0     113
Permanent Ineff=
       F       F
Bank Sta=4941.1,5109.1
Exp/Cntr=0.5,0.3

Type RM Length L Ch R = 3 ,9204.9  ,,,
BEGIN DESCRIPTION:
LOUETTA ROAD; Photo shows a bit smaller roadway length of approx. 90'- leave 117 deck length from survey for now VRR
Need picture of Louetta VRR
Structure ID: K131-00-00-S2
END DESCRIPTION:
Bridge Culvert--1,0,-1,-1, 0
Deck Dist Width WeirC Skew NumUp NumDn MinLoCord MaxHiCord MaxSubmerge Is_Ogee
10,117,2.6,0, 51, 51, , , 0.95, 0, ,,,
  3849.2  4059.2  4069.2  4079.2  4089.2  4129.2  4219.2  4239.2  4359.2  4369.2
  4375.6  4379.2  4399.2  4409.2  4465.6  4475.6  4489.2  4499.2  4605.6  4615.6
  4639.2  4649.2  4659.2  4699.2  4735.6  4759.2  4766.9  4769.2  4773.8  4776.9
  4820.9  4868.5  4926.7  4941.1    4946 4950.79  4950.9 4952.21  4952.3 5098.84
  5100.4 5100.51  5109.1  5253.6  5294.9    5321  5392.6  5452.6  5662.6  5792.6
    6031
   116.1     115   114.6   114.9   114.3   114.3   113.8     114   112.6     113
   113.8   113.8   113.8   113.8   113.8   113.3  113.29  113.28   113.2   112.9
  112.76   112.7  112.65  112.41   112.2  112.58   112.7  112.63  112.49   112.4
  112.22  112.35  113.17  113.45  113.54  113.63  118.73  118.73  118.73  118.75
  118.75  113.65  113.63  113.33   113.8   114.1  113.71  115.31  115.78  116.77
   119.4
   116.1     115   114.6   114.9   114.3   114.3   113.8     114   112.6     113
  112.62   112.4   112.7   112.4  112.19  112.15   112.1   112.5   112.2  112.17
   112.1   111.6   111.9   111.3  111.06   110.9  111.29   111.4  112.26  112.25
  112.09  111.93  111.72   111.3  109.56  107.56  107.52  106.97  110.63  110.65
  110.84  110.85  111.89  112.96  113.26  113.22   113.1   115.3   115.5   116.7
   119.4
  3849.2  4059.2  4069.2  4079.2  4089.2  4129.2  4219.2  4239.2  4359.2  4369.2
  4375.6  4379.2  4399.2  4409.2  4465.6  4475.6  4489.2  4499.2  4605.6  4615.6
  4639.2  4649.2  4659.2  4699.2  4735.6  4759.2  4766.9  4769.2  4773.8  4776.9
  4820.9  4868.5  4926.7  4941.1    4946 4950.79  4950.9 4952.21  4952.3 5098.84
  5100.4 5100.51  5109.1  5253.6  5294.9    5321  5392.6  5452.6  5662.6  5792.6
    6031
   116.1     115   114.6   114.9   114.3   114.3   113.8     114   112.6     113
   113.8   113.8   113.8   113.8   113.8   113.3  113.29  113.28   113.2   112.9
  112.76   112.7  112.65  112.41   112.2  112.58   112.7  112.63  112.49   112.4
  112.22  112.35  113.17  113.45  113.54  113.63  118.73  118.73  118.73  118.75
  118.75  113.65  113.63  113.33   113.8   114.1  113.71  115.31  115.78  116.77
   119.4
   116.1     115   114.6   114.9   114.3   114.3   113.8     114   112.6     113
  112.62   112.4   112.7   112.4  112.19  112.15   112.1   112.5   112.2  112.17
   112.1   111.6   111.9   111.3  111.06   110.9  111.29   111.4  112.26  112.25
  112.09  111.93  111.72   111.3  109.56  107.56  107.52  106.97  110.63  110.65
  110.84  110.85  111.89  112.96  113.26  113.22   113.1   115.3   115.5   116.7
   119.4
Pier Skew, UpSta & Num, DnSta & Num=  ,5001.3, 2 ,5001.3, 2 , 0 , 0 , 0 ,,
     1.3     1.3
   91.37  111.62
     1.3     1.3
   94.38  114.63
Pier Skew, UpSta & Num, DnSta & Num=  ,5052.5, 2 ,5052.5, 2 , 0 , 0 , 0 ,,
     1.3     1.3
  100.01  111.63
     1.3     1.3
  103.02  114.64
BR Coef= 1 , 1 , 1 ,1.25, 0 ,,,0.8,0,2,0,
WSPro=,,,, 1 ,,,, 0 ,,,, 0 ,,,,-1 ,-1 ,-1 , 0 , 0 , 0 , 0 , 0
BC Design=,, 0 ,, 0 ,,,,,,
BC HTab HWMax=126.53

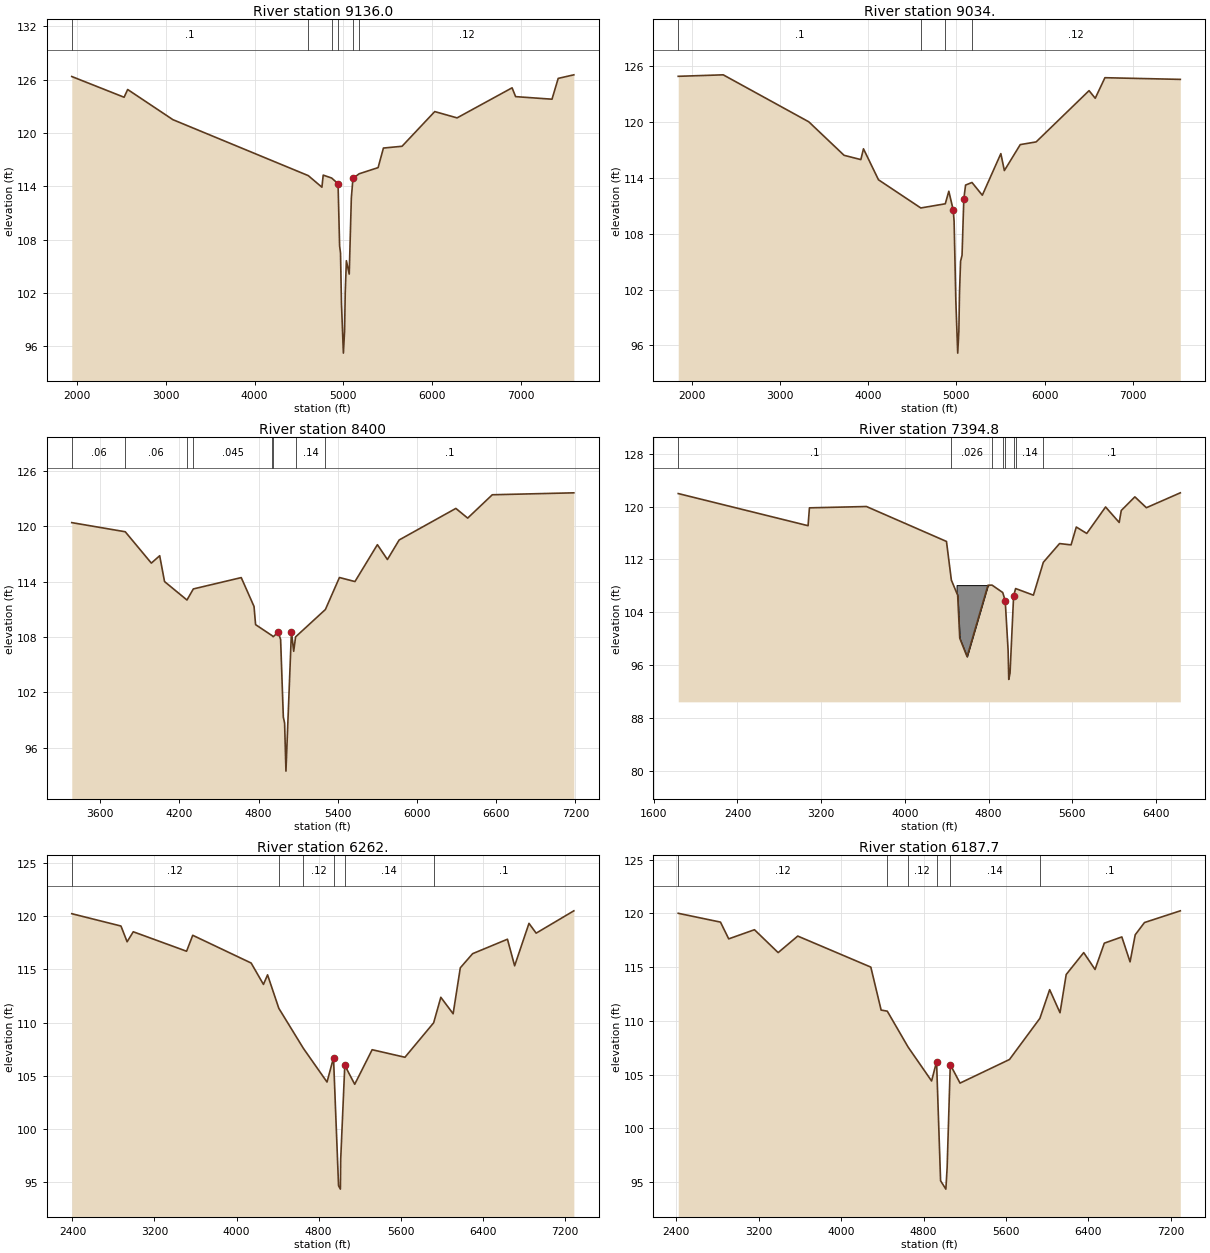
Type RM Length L Ch R = 1 ,9136.0  ,138.2,102,15.7
BEGIN DESCRIPTION:
Downstream Section of Bridge/Culvert/Weir
END DESCRIPTION:
XS GIS Cut Line= 4
      3076149.81     13940338.21      3073709.69     13938636.21
      3073539.78     13938524.32      3071071.35     13938190.97
#Sta/Elev= 30
  1939.4  126.34  2529.4  124.01  2569.4  124.88  3079.4  121.49  4605.6   115.2
  4759.2   113.9  4773.8  115.26  4868.5  114.93  4941.1   114.3  4958.6  107.31
  4968.9   106.5  4979.7  100.82  5001.3   95.25  5014.8   97.73  5022.2  102.08
  5034.9  105.64  5067.1  104.13  5090.9  112.69  5109.1  114.89  5179.5  115.41
  5392.6   116.1  5452.6   118.3  5662.6   118.5    6031   122.4  6282.8  121.69
  6902.8  125.07  6942.8  124.08  7352.8  123.79  7422.8  126.13  7599.1  126.53
#Mann= 6 ,-1 , 0
  1939.4      .1       0  4605.6     .12       0  4868.5     .04       0
  4941.1     .04       0  5109.1     .04       0  5179.5     .12       0
#XS Ineff= 2 , 0
       0    4937     112    5099       0     112
Permanent Ineff=
       F       F
Bank Sta=4941.1,5109.1
Exp/Cntr=0.5,0.3

Type RM Length L Ch R = 1 ,9034.   ,597.37,634,647.19
BEGIN DESCRIPTION:
K131-00-00-S2_LOUETTA_DS - XS 1
END DESCRIPTION:
XS GIS Cut Line= 4
        3076109.       13940249.       3073863.1     13938450.32
      3073497.45     13938505.45      3071075.43     13938174.81
#Sta/Elev= 30
    1847  124.92    2357  125.08    3327  120.03    3727  116.43    3917  115.97
    3947  117.13    4117   113.8    4597  110.77  4874.4  111.22  4914.4  112.57
  4964.4  110.56  4974.4  109.33 4994.19  100.75 5015.24   95.17 5028.29   97.52
 5035.44  101.64 5047.72  105.04  5064.4  105.69  5084.4  111.73  5104.2  113.23
    5177  113.51  5294.2  112.14  5504.2  116.61  5544.2  114.79  5724.2  117.58
  5904.2  117.87  6504.2  123.38  6574.2  122.56  6684.2  124.77  7538.7  124.59
#Mann= 4 ,-1 , 0
    1847      .1       0    4597     .12       0  4874.4     .04       0
    5177     .12       0
Bank Sta=4964.4,5084.4
Exp/Cntr=0.3,0.1

Type RM Length L Ch R = 1 ,8400    ,710,1005.2,900
BEGIN DESCRIPTION:
Added XS
END DESCRIPTION:
XS GIS Cut Line= 6
     3074902.902     13938673.34     3073893.828     13937988.17
     3073560.901     13937969.73     3073172.002     13937873.01
     3073039.386     13937842.11     3071324.798     13937857.33
#Sta/Elev= 30
 3383.79  120.39    3789   119.4 3986.79     116    4050   116.8 4086.79     114
 4256.79     112    4305   113.2    4668  114.43    4765   111.3 4776.79  109.33
 4902.48  108.13 4909.78  108.02 4948.07   108.5 4966.39  107.73 4987.03   99.31
 4996.66   98.66 5006.79   93.45 5048.51  108.57 5065.61  106.44 5079.79     108
 5305.71  110.97 5412.21  114.44 5529.79     114 5699.79     118 5775.74  116.39
 5864.84  118.51 6294.35  121.93 6384.03  120.88 6570.41  123.41 7188.51  123.62
#Mann= 8 ,-1 , 0
 3383.79     .06       0    3789     .06       0 4256.79     .14       0
    4305    .045       0 4902.48     .14       0 4909.78    .045       0
 5079.79     .14       0 5305.71      .1       0
Bank Sta=4948.07,5048.51
Exp/Cntr=0.3,0.1

Type RM Length L Ch R = 1 ,7394.8  ,1139,1132.8,1106.8
BEGIN DESCRIPTION:
Cross Section K131-00-00-X01
END DESCRIPTION:
XS GIS Cut Line= 5
      3075826.47     13938592.26      3075605.71     13938054.75
      3073333.65     13936962.79      3073220.37     13936914.24
      3071708.74     13937354.06
#Sta/Elev= 30
  1833.8  121.96  3074.9   117.1    3088   119.8    3633     120    4398  114.72
  4444.8  108.87  4504.9   106.6  4524.9   100.1  4594.9    97.3  4794.9   108.1
  4833.4  108.12  4935.7     107  4959.6  105.76  4987.4   98.18  4993.4   93.86
  5005.6    94.8  5039.8  106.48    5059   107.6    5229   106.6    5324  111.57
    5479   114.4    5589   114.2    5639   116.9    5739  115.93    5919  119.93
    6049  117.59    6069   119.4    6199  121.46    6309  119.82  6633.3  122.07
#Mann= 8 ,-1 , 0
  1833.8      .1       0  4444.8    .026       0  4833.4     .14       0
  4935.7    .045       0  4959.6    .055       0  5039.8    .045       0
    5059     .14       0    5324      .1       0
#Block Obstruct= 2 ,-1
 4494.26    4805  108.12    4806    4807      80
Bank Sta=4959.6,5039.8
Exp/Cntr=0.3,0.1

Type RM Length L Ch R = 1 ,6262.   ,45.1,74.3,84.9
BEGIN DESCRIPTION:
K131-00-00-S1A-DAM_US FIELD - XS 4
END DESCRIPTION:
XS GIS Cut Line= 4
       3075559.7      13938017.9      3073995.44     13936063.49
      3073790.54     13936034.68      3071854.97     13937054.19
#Sta/Elev= 30
    2393  120.24    2873  119.08    2933   117.6    2993  118.54    3513  116.71
    3573  118.21    4143   115.6    4263  113.59    4303  114.49    4413  111.34
    4653  107.57    4883  104.41  4946.4  106.69 4995.55   94.66 5013.43   94.34
  5016.4   97.11  5056.4  105.98  5153.3   104.2  5323.3  107.45  5643.3  106.74
  5923.3  109.98  5993.3  112.38  6113.3  110.83  6183.3  115.15  6303.3  116.48
  6643.3  117.84  6713.3  115.34  6853.3  119.33  6923.3  118.41  7290.9  120.51
#Mann= 6 ,-1 , 0
    2393     .12       0    4413     .06       0    4653     .12       0
  4946.4    .055       0  5056.4     .14       0  5923.3      .1       0
Bank Sta=4946.4,5056.4
Exp/Cntr=0.7,0.5

Type RM Length L Ch R = 1 ,6187.7  ,23,22.2,12.9
BEGIN DESCRIPTION:
Upstream Section of Bridge/Culvert/Weir
END DESCRIPTION:
XS GIS Cut Line= 4
      3075567.35     13937918.59      3073994.76     13936003.42
      3073798.18     13935935.34      3071862.62     13936954.84
#Sta/Elev= 30
  2419.1  120.01  2829.1  119.19  2909.1  117.63  3159.1  118.48  3389.1  116.35
  3579.1  117.89  4288.6     115  4388.6     111  4448.4   110.9  4650.9  107.55
  4878.6   104.4  4926.8   106.2  4965.8   95.11    5017   94.33  5029.3   96.31
  5059.9  105.92  5154.7   104.2  5634.7   106.4  5929.8  110.23  6024.7   112.9
  6125.2  110.75  6185.2  114.31  6355.2  116.35  6465.2  114.78  6555.2  117.23
  6725.2  117.81  6805.2  115.49  6855.2  118.01  6945.2  119.15  7292.9  120.24
#Mann= 6 ,-1 , 0
  2419.1     .12       0  4448.4     .06       0  4650.9     .12       0
  4926.8     .02       0  5059.9     .14       0  5929.8      .1       0
#XS Ineff= 2 , 0
       0    4923   104.5    5065       0   104.5
Permanent Ineff=
       F       F
Bank Sta=4926.8,5059.9
Exp/Cntr=0.7,0.5