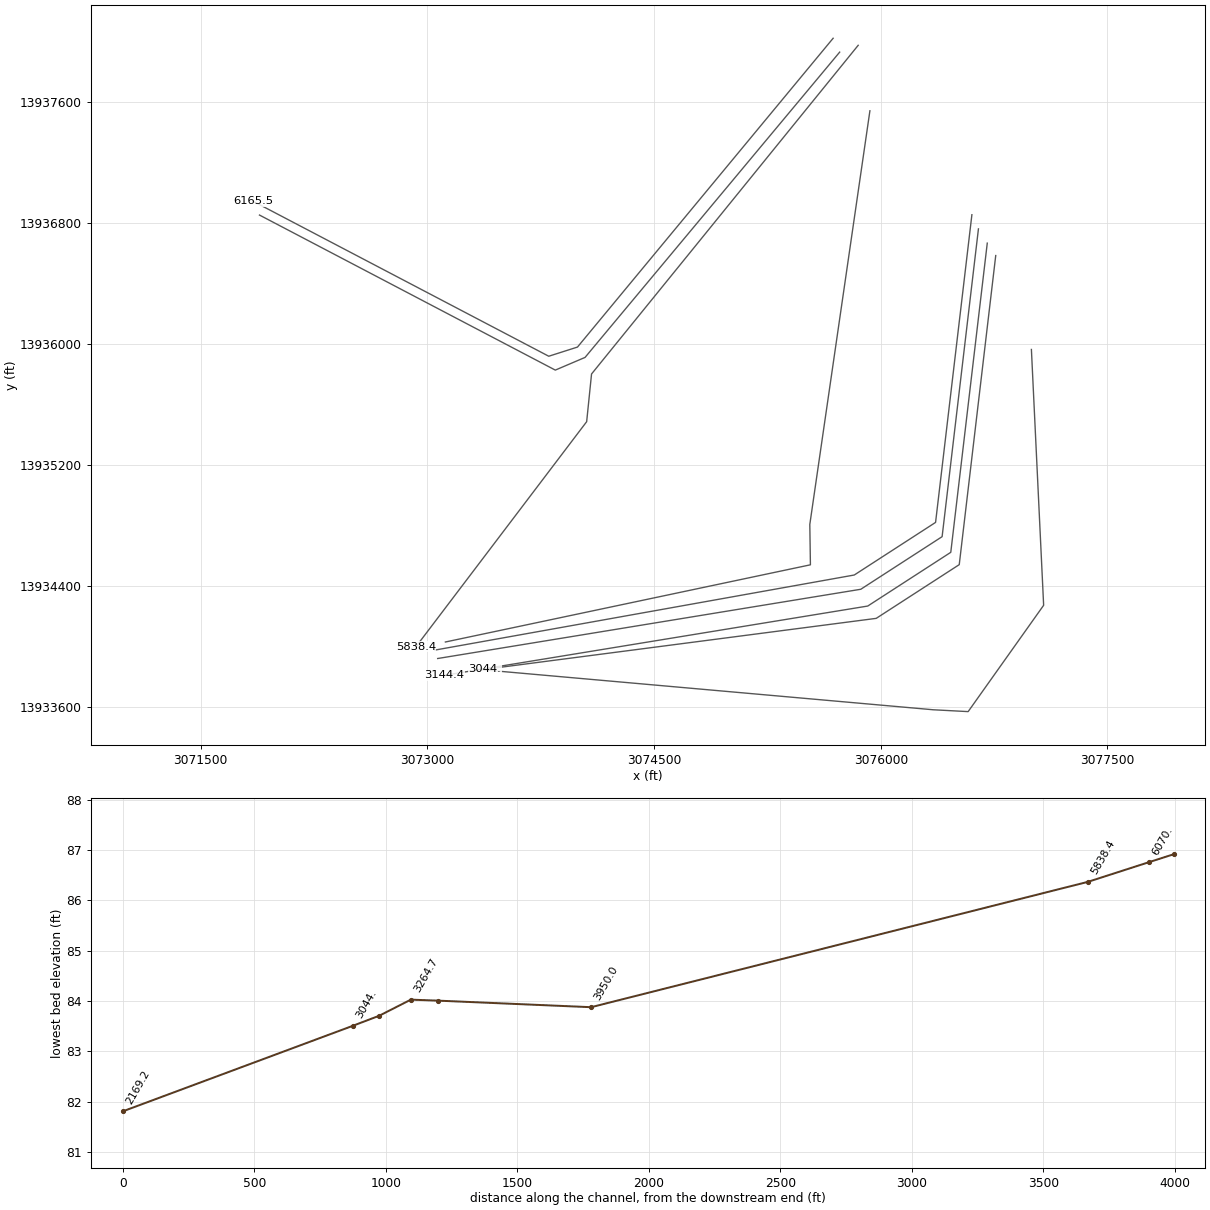
HEC-RAS study K131-00-00.prj: K131-00-00

--- K131-00-00.g04 (geometry) --- (continued)

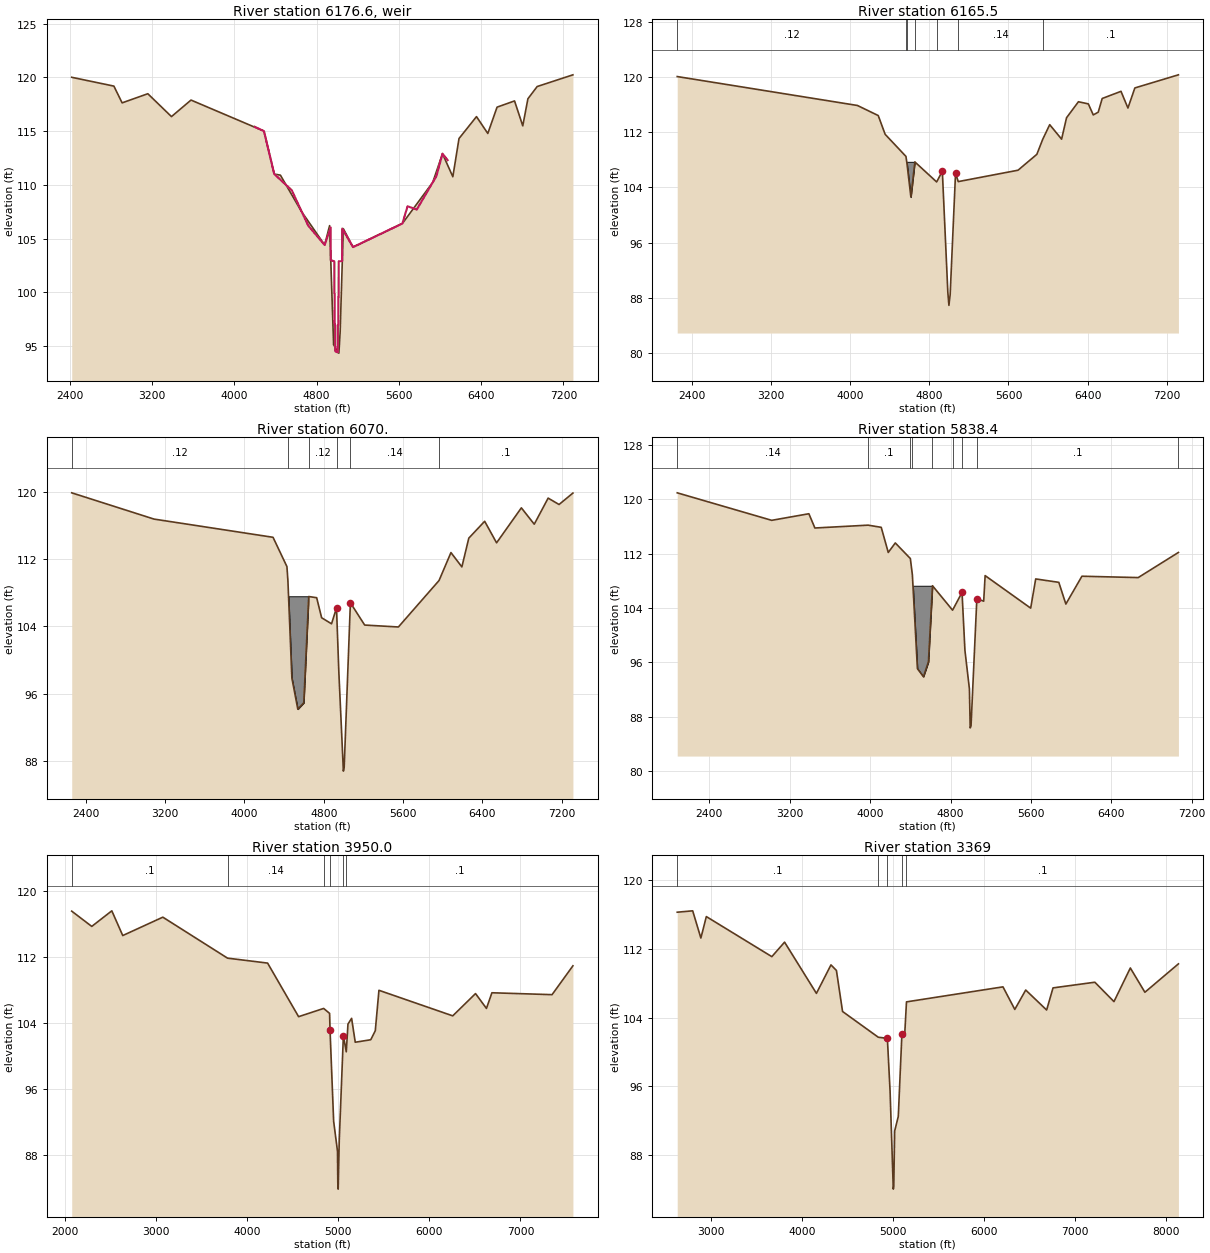
Type RM Length L Ch R = 5 ,6176.6  ,,,
BEGIN DESCRIPTION:
WEIR 300' US OF CONFLUENCE WITH K131-02-00
Structure ID: K131-00-00-S1A
END DESCRIPTION:
IW Pilot Flow=0
#Inline Weir SE= 30
  4198.6   115.4  4288.6     115  4388.6     111  4558.6   109.5  4718.6   106.2
  4878.6   104.4  4937.6  106.02  4937.7  102.99  4972.6  102.87 4972.71   99.92
  4975.7   99.84  4975.8   96.96  4981.2   96.97  4981.3   94.51  5006.4   94.39
  5006.5    96.9  5011.8   96.96 5011.91   99.56  5014.8   99.56    5015   99.88
  5015.2  102.87  5048.9   102.9  5049.2  105.93  5154.7   104.2  5634.7   106.4
  5684.7     108  5774.7   107.7  5964.7   110.8  6024.7   112.9  6074.7   112.3
IW Dist,WD,Coef,Skew,MaxSub,Min_El,Is_Ogee,SpillHt,DesHd
10,1,3,0,0.95,, 0 ,,,0,0,

Type RM Length L Ch R = 1 ,6165.5  ,98.1,95.5,61.6
BEGIN DESCRIPTION:
Cross Section FIELD_DS
Located At: WEIR 300' US OF CONFLUENCE WITH K100-00-00
END DESCRIPTION:
XS GIS Cut Line= 4
      3075684.87     13938022.25       3073993.1     13935979.67
      3073802.95     13935918.99      3071845.41     13936944.51
#Sta/Elev= 30
  2254.8  120.07  4074.8  115.88  4284.8  114.42  4354.8   111.7  4564.8   108.5
  4574.8   107.5  4614.8   102.6  4654.8   107.7  4874.8   104.8  4932.3  106.36
  4987.8    88.8  4998.8   86.92  5011.3    88.5  5065.5  106.06    5093  104.85
  5696.6   106.5  5886.6   108.8  5946.1  110.98  6016.6   113.1  6136.6     111
  6186.6   114.1  6306.6  116.42  6406.6  116.11  6456.6  114.51  6506.6  114.91
  6546.6  116.89  6736.6  117.93  6806.6  115.51  6876.6  118.42  7316.5  120.32
#Mann= 7 ,-1 , 0
  2254.8     .12       0  4564.8     .06       0  4574.8    .026       0
  4654.8     .12       0  4874.8    .055       0    5093     .14       0
  5946.1      .1       0
#Block Obstruct= 2 ,-1
 4564.73 4654.85  107.72    4655    4656      80
Bank Sta=4932.3,5065.5
Exp/Cntr=0.7,0.5

Type RM Length L Ch R = 1 ,6070.   ,119.9,231.6,232
BEGIN DESCRIPTION:
K131-00-00-S1A-DAM_DS FIELD - XS 1
END DESCRIPTION:
XS GIS Cut Line= 4
      3075728.17      13937930.5      3074043.21     13935911.23
      3073846.26     13935827.28      3071888.72     13936852.81
#Sta/Elev= 30
  2258.5  119.93  3088.5   116.8  4288.5  114.63  4428.5  111.14  4438.5  109.47
  4478.5   97.85  4538.5   94.14  4598.5    94.9  4648.5  107.57  4728.5  107.43
  4778.5  105.04  4878.5  104.32  4928.5  106.22 4952.39   98.48 4997.95   86.76
  5006.2   87.28  5068.5  106.83  5212.6  104.17  5552.6  103.94  5962.6  109.48
  6082.6  112.81  6192.6   111.1  6262.6  114.53  6422.6  116.54  6542.6  113.97
  6792.6  118.14  6922.6  116.19  7062.6   119.3  7172.6  118.54  7312.5   119.9
#Mann= 6 ,-1 , 0
  2258.5     .12       0  4438.5    .026       0  4648.5     .12       0
  4928.5    .055       0  5068.5     .14       0  5962.6      .1       0
#Block Obstruct= 1 ,-1
    4387 4644.82   107.6
Bank Sta=4928.5,5068.5
Exp/Cntr=0.3,0.1

Type RM Length L Ch R = 1 ,5838.4  ,1818.4,1888.4,1890
BEGIN DESCRIPTION:
Cross Section K131-00-00-X0C; Detention pond on left VRR
END DESCRIPTION:
XS GIS Cut Line= 4
      3075850.67     13937975.62      3074086.15     13935801.66
      3074053.79     13935486.09      3072923.15     13933996.26
#Sta/Elev= 30
  2080.5  120.98  3020.5  116.93  3390.5   117.9  3450.5   115.8  3980.1  116.22
  4110.5   115.9  4180.5   112.2  4250.5   113.6  4400.5   111.3  4420.5   108.9
  4470.5    95.1  4530.5    93.9  4580.5    96.1  4620.5   107.3  4820.5   103.7
  4914.6  106.32  4943.6   97.76  4988.1   92.11  4995.9   86.37  5004.1   86.65
  5062.1  105.41  5130.1  105.02  5144.4  108.79  5597.7     104  5647.7   108.3
  5877.7   107.8  5947.7   104.6  6107.7   108.7  6667.7   108.5  7067.9   112.2
#Mann= 9 ,-1 , 0
  2080.5     .14       0  3980.1      .1       0  4400.5     .06       0
  4420.5    .026       0  4620.5     .14       0  4820.5    .045       0
  4914.6    .055       0  5062.1      .1       0  7067.9     .99       0
#Block Obstruct= 2 ,-1
    4410  4620.5   107.3    4621    4622      80
Bank Sta=4914.6,5062.1
Exp/Cntr=0.3,0.1

Type RM Length L Ch R = 1 ,3950.0  ,780,581,502
BEGIN DESCRIPTION:
Cross Section K131-00-00-X0B
END DESCRIPTION:
XS GIS Cut Line= 4
      3075928.23     13937542.48      3075530.48     13934806.41
      3075534.53     13934539.39      3073118.92     13934028.81
#Sta/Elev= 30
  2075.3   117.6  2295.3  115.75  2515.3  117.64  2635.3  114.64  3075.3  116.87
  3785.3   111.9  4225.3   111.3  4565.3   104.8  4840.3   105.8  4905.5   105.2
  4910.6  103.13  4950.1   92.11  4992.4   88.47  4995.7   84.66  4999.8   83.88
  5011.8   89.85  5056.9  102.51  5088.7  100.54  5107.2   103.9  5147.2   104.6
  5187.2   101.7  5357.2     102  5407.2   103.1  5447.2     108  6257.2   104.9
  6507.2   107.6  6627.2   105.8  6687.2   107.7  7347.2  107.47  7576.2  110.97
#Mann= 6 ,-1 , 0
  2075.3      .1       0  3785.3     .14       0  4840.3    .045       0
  4910.6    .055       0  5056.9    .045       0  5088.7      .1       0
Bank Sta=4910.6,5056.9
Exp/Cntr=0.3,0.1

Type RM Length L Ch R = 1 ,3369    ,103,104.3,106.9
BEGIN DESCRIPTION:
K131-00-00-S01_US - XS 4
END DESCRIPTION:
XS GIS Cut Line= 4
       3076603.1       13936855.      3076362.73     13934819.85
      3075824.65     13934471.92       3073050.3     13933975.44
#Sta/Elev= 30
  2626.5  116.28  2796.5  116.44  2886.5  113.27  2946.5  115.77  3666.5   111.1
  3806.5  112.79  4156.5  106.82  4316.5  110.14  4376.5  109.49  4443.8  104.71
  4836.4  101.71  4936.4  101.58  4966.4   95.38 5001.58   84.01 5006.99   84.37
  5016.4   90.78  5056.4   92.48  5096.4  102.14  5126.4  101.91  5146.4  105.83
  6207.1  107.58  6337.1  104.95  6457.1  107.21  6687.1  104.88  6757.1  107.46
  7217.1  108.12  7427.1  105.86  7607.1  109.78  7767.1  106.95  8135.6  110.26
#Mann= 5 ,-1 , 0
  2626.5      .1       0  4836.4    .045       0  4936.4    .055       0
  5096.4    .045       0  5146.4      .1       0
Bank Sta=4936.4,5096.4
Exp/Cntr=0.5,0.3

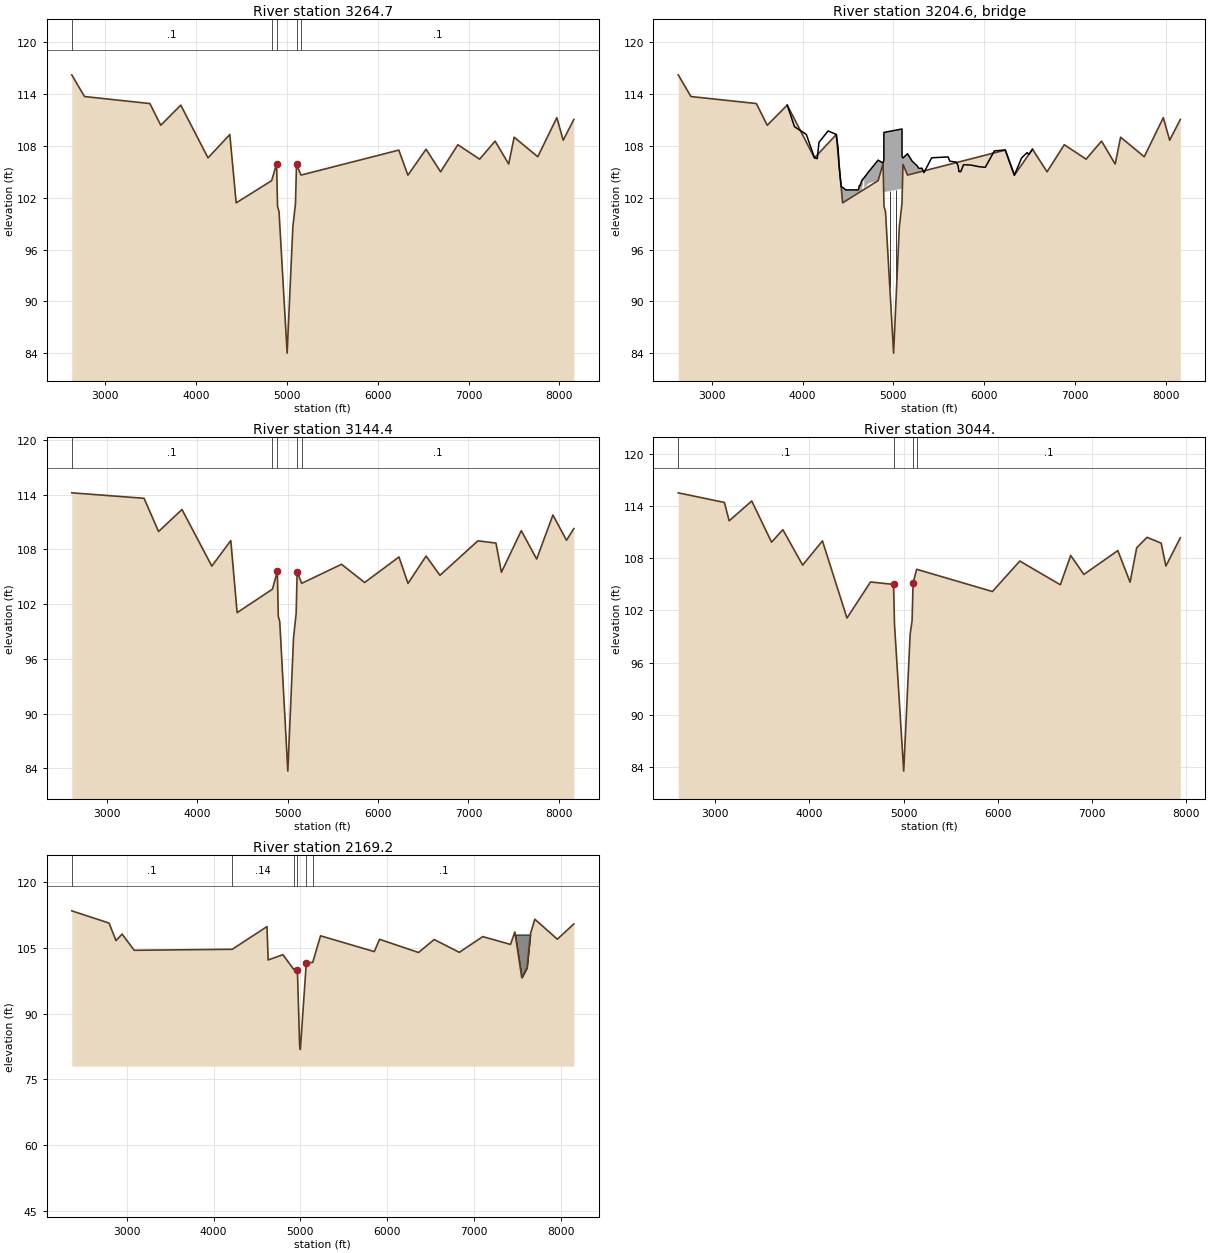
Type RM Length L Ch R = 1 ,3264.7  ,121,120.3,118.3
BEGIN DESCRIPTION:
Upstream Section of Bridge/Culvert/Weir
END DESCRIPTION:
XS GIS Cut Line= 4
      3076646.41     13936761.32      3076406.04      13934725.6
      3075867.95     13934377.67      3073067.97     13933919.62
#Sta/Elev= 30
  2630.8   116.2  2770.8  113.69  3490.8  112.88  3610.8  110.37  3830.9   112.7
  4130.9   106.6  4370.9   109.3  4440.9   101.4  4831.6  103.97    4886  105.92
  4896.4     101  4912.6   100.4  5001.9   84.03    5065   98.62    5094  101.33
  5105.1  105.85  5155.1  104.61  6231.5   107.5  6331.5   104.6  6531.5   107.6
  6691.4  104.99  6881.4  108.12  7121.4  106.45  7291.4  108.54  7441.4  105.89
  7501.4  108.99  7761.4  106.73  7971.4  111.25  8041.4  108.64  8158.6  111.04
#Mann= 5 ,-1 , 0
  2630.8      .1       0  4831.6    .045       0    4886    .055       0
  5105.1    .045       0  5155.1      .1       0
#XS Ineff= 2 , 0
       0  4870.9   104.3 5121.15       0  104.43
Permanent Ineff=
       F       F
Bank Sta=4886,5105.1
Exp/Cntr=0.5,0.3

Type RM Length L Ch R = 3 ,3204.6  ,,,
BEGIN DESCRIPTION:
CYPRESSWOOD
Structure ID: K131-00-00-S01
END DESCRIPTION:
Bridge Culvert--1,0,-1,-1, 0
Deck Dist Width WeirC Skew NumUp NumDn MinLoCord MaxHiCord MaxSubmerge Is_Ogee
10,96,2.6,0, 60, 60, , , 0.95, 0, ,,,
  3830.9  3910.9  4040.9  4130.9  4160.9  4180.9  4280.9  4370.9  4390.9  4400.9
  4424.3  4430.9  4440.9  4474.3  4510.9  4530.9  4614.3  4624.3  4634.3  4650.9
  4678.3    4679  4728.5    4831  4884.6    4886 4892.93 4894.69  4894.8  5094.8
 5094.91 5098.22  5105.2  5155.2  5206.8  5260.7  5277.4  5315.3  5315.7    5336
  5351.5  5421.5  5601.5  5621.5  5691.5  5711.5  5721.5  5741.5  5771.5  5851.5
  5871.5  5941.5  6011.5  6111.5  6231.5  6331.5  6411.5  6471.5  6491.5  6531.5
   112.7   110.2  109.31  106.61  106.51  108.41  109.71  109.31  107.71  105.81
   103.3  103.26  103.19   102.9   102.9   102.9   102.9   103.4   103.4  103.98
  104.32  104.33  105.01  106.34  106.01  106.06  106.28  106.34  109.54  109.94
  106.74  106.69  106.59  107.08  106.21  105.69   105.4  105.39   105.4   104.9
  105.21  106.61  106.71  106.21  106.11  105.71  105.01  105.01  105.81  105.77
  105.73  105.58  105.51  107.41  107.51   104.6   106.6   107.2     107   107.6
   112.7   110.2   109.3   106.6   106.5   108.4   109.7   109.3   107.7   105.8
  102.76   101.9   101.4  101.26   101.1   101.7  102.05  102.09  102.13   102.2
   104.3  103.09  103.67  103.95  105.58  105.92  102.64  102.64  102.64  103.04
  103.04  103.05  105.89  104.61  103.43  103.63  104.07  105.07   104.1  104.52
   105.2   106.6   106.7   106.2   106.1   105.7     105     105   105.8   104.7
   105.1     105   105.5   107.4   107.5   104.6   106.6   107.2     107   107.6
  3830.9  3910.9  4040.9  4130.9  4160.9  4180.9  4280.9  4370.9  4390.9  4400.9
  4424.3  4474.3  4614.3  4624.3  4634.3  4654.3  4674.3  4727.3  4727.4  4780.2
  4831.6  4884.5    4886 4892.84 4894.69  4894.8  5077.6  5094.8 5094.91 5098.33
  5105.1  5155.2  5208.2    5261  5277.4  5287.4  5307.4    5316    5336  5341.5
  5351.5  5421.5  5601.5  5621.5  5691.5  5711.5  5721.5  5741.5  5771.5  5777.1
  5817.1  5941.5  6011.5  6111.5  6231.5  6331.5  6411.5  6471.5  6491.5  6531.5
   112.7   110.2  109.31  106.61  106.51  108.41  109.71  109.31  107.71  105.81
   103.3   102.9   102.9   103.4   103.4   104.1   104.2  105.18     105  105.58
  106.35  106.01  106.06  106.28  106.34  109.54  109.91  109.94  106.74  106.69
  106.59  107.08  106.19  105.69   105.4   105.6   105.3   105.4   104.9   104.9
  105.21  106.61  106.71  106.21  106.11  105.71  105.01  105.01  105.81  105.73
   105.9  105.58  105.51  107.41  107.51   104.6   106.6   107.2     107   107.6
                                                                                
                                                                                
                          102.68  102.64  102.64  103.01  103.04  103.04  103.09
                                                                                
                                                                                
                                                                                
Pier Skew, UpSta & Num, DnSta & Num=  ,4960.3, 2 ,4960.3, 2 , 0 , 0 , 0 ,,
     1.5     1.5
   89.91  103.77
     1.5     1.5
   89.61  103.47
Pier Skew, UpSta & Num, DnSta & Num=  ,5030.3, 2 ,5030.3, 2 , 0 , 0 , 0 ,,
     1.5     1.5
   89.25  103.91
     1.5     1.5
   88.95  103.61
BR Coef= 1 , 1 , 1 ,1.25, 0 ,,,0.8,0,2,0,
WSPro=,,,, 1 ,,,, 0 ,,,, 0 ,,,,-1 ,-1 ,-1 , 0 , 0 , 0 , 0 , 0
BC Design=,, 0 ,, 0 ,,,,,,
BC HTab HWMax=116.2

Type RM Length L Ch R = 1 ,3144.4  ,101,100.4,99
BEGIN DESCRIPTION:
Downstream Section of Bridge/Culvert/Weir
END DESCRIPTION:
XS GIS Cut Line= 4
      3076704.82     13936667.05      3076463.34     13934621.99
      3075913.85     13934266.68      3073109.74     13933807.95
#Sta/Elev= 30
  2611.4  114.21  3411.4  113.61  3571.4  109.97  3830.9  112.38  4160.9  106.18
  4370.9  108.98  4440.9  101.08  4831.6  103.65    4886   105.6  4896.4  100.68
  4912.6  100.08  5001.9   83.71    5065    98.3    5094  101.01  5105.1  105.53
  5155.1  104.29    5596  106.38  5851.5  104.38  6231.5  107.18  6331.5  104.28
  6531.5  107.28    6685  105.17    7105  108.95    7305   108.7    7365   105.5
    7585  110.06    7755  106.95    7935  111.78    8085  109.01  8166.4  110.29
#Mann= 5 ,-1 , 0
  2611.4      .1       0  4831.6    .045       0    4886    .055       0
  5105.1    .045       0  5155.1      .1       0
#XS Ineff= 2 , 0
       0 4877.85  104.62 5107.25       0  104.56
Permanent Ineff=
       F       F
Bank Sta=4886,5105.1
Exp/Cntr=0.5,0.3

Type RM Length L Ch R = 1 ,3044.   ,875,874.75,787.2
BEGIN DESCRIPTION:
K131-00-00-S01_DS - XS 1
END DESCRIPTION:
XS GIS Cut Line= 4
      3076760.86       13936585.      3076519.39     13934540.47
       3075969.9     13934185.16       3073378.9     13933848.03
#Sta/Elev= 30
  2609.7  115.54  3099.7  114.43  3149.7  112.32  3389.7   114.6  3599.7  109.86
  3719.7   111.3  3929.7  107.22  4139.7  110.01  4399.7  101.13  4649.7  105.28
 4894.25     105 4903.89  100.43 5001.67   83.51 5070.03   99.25 5090.58  100.83
  5101.3  105.12  5101.4  105.15    5139  106.74  5943.3  104.18  6233.3  107.69
  6663.3  104.96  6773.3  108.33  6913.3  106.15  7273.3  108.89  7403.3  105.26
  7473.3  109.21  7583.3  110.42  7733.3  109.75  7783.3  107.11  7936.2  110.37
#Mann= 4 ,-1 , 0
  2609.7      .1       0 4894.25    .055       0  5101.4    .045       0
    5139      .1       0
Bank Sta=4894.25,5101.3
Exp/Cntr=0.3,0.1

Type RM Length L Ch R = 1 ,2169.2  ,0,0,0
BEGIN DESCRIPTION:
Cross Section K131-00-00-X0A
END DESCRIPTION:
XS GIS Cut Line= 5
      3076996.91     13935963.76      3077077.87     13934271.69
      3076578.33     13933568.41      3076347.72     13933580.55
       3073359.4      13933845.8
#Sta/Elev= 30
  2364.8  113.39  2794.8   110.6  2874.8   106.6  2944.8   108.1  3084.8   104.4
  4214.7  104.63  4615.1   109.8  4628.8   102.2  4798.8   103.4  4921.4   100.1
  4966.1    99.8  4991.6   82.61  4999.7   81.81  5068.2  101.51  5142.5  101.65
  5232.4   107.7  5852.4   104.1  5912.4   106.9  6362.4   103.9  6542.4  106.85
  6832.4  103.94  7102.4  107.52  7422.4  105.74  7472.4  108.57  7552.4   98.17
  7612.4  100.41  7652.4  108.14  7702.4  111.48  7962.4  106.93  8152.4  110.41
#Mann= 6 ,-1 , 0
  2364.8      .1       0  4214.7     .14       0  4921.4    .045       0
  4966.1    .055       0  5068.2    .045       0  5142.5      .1       0
#Block Obstruct= 2 ,-1
  7472.3    7653     108    7655    7656      50
Bank Sta=4966.1,5068.2
Exp/Cntr=0.3,0.1

Chan Stop Cuts=-1
Use User Specified Reach Order=0
User Specified Reach Order=K131-00-00      ,K131-00-00_0022